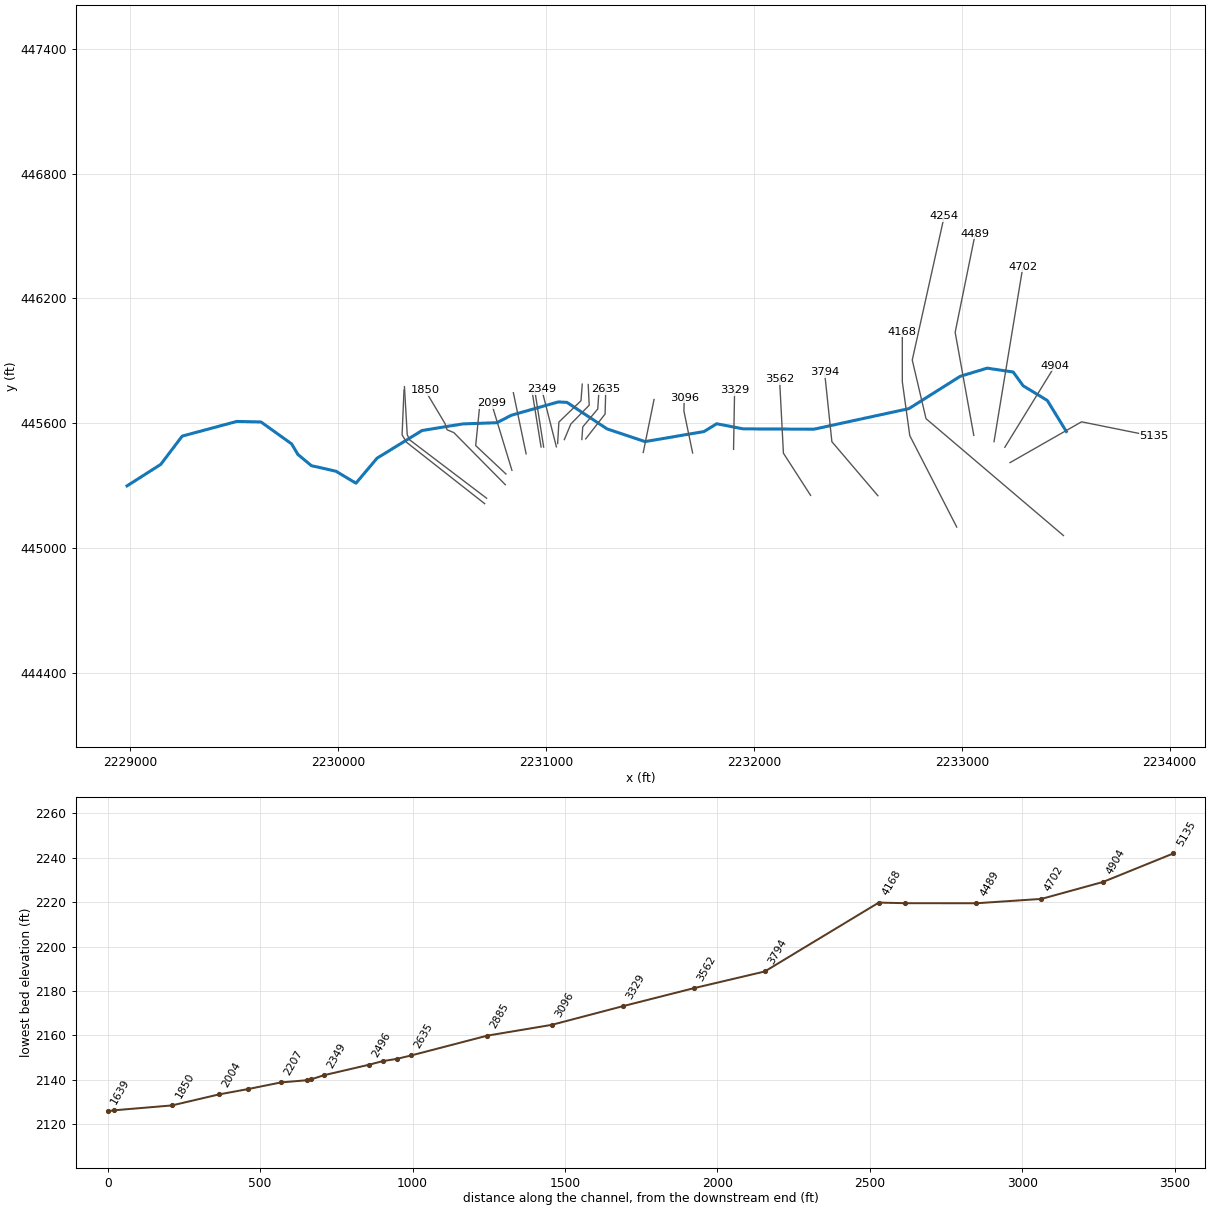
--- MARLNRN.prj (project) ---

Proj Title=MARLNRN
Current Plan=p01
Default Exp/Contr=0,0
English Units
Geom File=g01
Flow File=f01
Plan File=p01
Background Map Layer=Inundation Boundary (01pct Value_0)
BEGIN DESCRIPTION:
----------MODEL BY WOOD PLC 2021----------
Stream Name: Marlin Run
Flood Zone: Enhanced Approximate
Pocahontas County, WV
HEC-RAS Version: RAS 6.1
Vertical Datum: NAVD88
Projection: NAD 1983 StatePlane West Virginia S FIPS 4702 (US Feet)
Terrain: 1-meter LIDAR (FEMA Region III 3DEP collected 2016-2018)
Land Use: 2019 NLCD
Hydrologic Method:
WV SIR2010-5033 regression equations
Model Notes:
Flood control structure at RS 1100.
Normal depth tie in with Knapp Creek.
END DESCRIPTION:
DSS Export Rating Curves= 0
DSS Export Rating Curve Sorted= 0
DSS Export Volume Flow Curves= 0
DXF OffsetX= 0
DXF OffsetY= 0
DXF ScaleX= 0
DXF ScaleY= 0

--- MARLNRN.p01 (plan) ---

Plan Title=Floodplain
Program Version=6.10
Short Identifier=Floodplain
Geom File=g01
Flow File=f01
Subcritical Flow
K Sum by GR= 0
Std Step Tol= 0.01
Critical Tol= 0.01
Num of Std Step Trials= 20
Max Error Tol= 0.3
Flow Tol Ratio= 0.001
Split Flow NTrial= 30
Split Flow Tol= 0.02
Split Flow Ratio= 0.02
Log Output Level= 0
Friction Slope Method= 1
Unsteady Friction Slope Method= 2
Unsteady Bridges Friction Slope Method= 1
Parabolic Critical Depth
Global Vel Dist= 0 , 0 , 0
Global Log Level= 0
CheckData=True
Encroach Param=-1 ,0,0, 0
Mapping Interval=1HOUR
Computation Time Step Use Courant=        0
Computation Time Step Use Time Series=    0
Computation Time Step Count To Double=0
Computation Time Step Max Doubling=0
Computation Time Step Max Halving=0
Computation Time Step Residence Courant=0
Run HTab= 0
Run UNet= 0
Run Sediment= 0
Run PostProcess= 0
Run WQNet= 0
Run RASMapper=-1
UNET Theta= 0
UNET Theta Warmup= 0
UNET ZTol= 0
UNET ZSATol= 0
UNET MxIter= 0
UNET Max Iter WO Improvement= 0
UNET MaxInSteps= 0
UNET DtIC= 0
UNET DtMin= 0
UNET MaxCRTS= 0
UNET WFStab= 0
UNET SFStab= 0
UNET WFX= 1
UNET SFX= 1
UNET Gravity=32.174
UNET 1D Methodology=Finite Difference
UNET DSS MLevel= 1
UNET Pardiso=0
UNET DZMax Abort= 0
UNET Use Existing IB Tables= 0
UNET Froude Reduction=False
UNET Froude Limit= 0
UNET Froude Power= 0
UNET D1 Cores= 0
UNET WindReference=Eulerian
UNET WindDragFormulation=Hsu (1988)
UNET D2 Coriolis=0
UNET D2 Cores= 0
UNET D2 Theta= 1
UNET D2 Theta Warmup= 1
UNET D2 Z Tol= 0.01
UNET D2 Volume Tol= 0.01
UNET D2 Max Iterations= 20
UNET D2 Equation= 0
UNET D2 RampUpFraction=0.1
UNET D2 TimeSlices= 1
UNET D2 Turbulence Formulation=Non-Conservative (original)
UNET D2 Eddy Viscosity=0.3
UNET D2 Transverse Eddy Viscosity=0.1
UNET D2 Smagorinsky Mixing=0
UNET D2 BCVolumeCheck=0
UNET D2 Cores=0
UNET D2 SolverType=PARDISO (Direct)
UNET D2 Minimum Iterations= 2147483647
UNET D2 Maximum Iterations= 2147483647
UNET D2 Restart Number= 10
UNET D2 Relaxation Coeff=1.3
UNET D2 SOR Precondition Iterations= 10
UNET D2 ILUT Maximum Fill= 8
UNET D2 ILUT Tolerance=1E-08
UNET D1D2 MaxIter= 0
UNET D1D2 ZTol=0.01
UNET D1D2 QTol=0.1
UNET D1D2 MinQTol=1
Write IC File= 0
Write IC File at Fixed DateTime=0
Write IC File at Sim End=0
Echo Input=False
Echo Parameters=False
Echo Output=False
Write Detailed= 0
HDF Write Warmup=0
HDF Write Time Slices=0
HDF Flush=0
HDF Compression= 1
HDF Chunk Size= 1
HDF Spatial Parts= 1
HDF Use Max Rows=0
HDF Fixed Rows= 1
Calibration Method= 0
Calibration Iterations= 20
Calibration Max Change=0.05
Calibration Tolerance=0.2
Calibration Maximum=1.5
Calibration Minimum=0.5
Calibration Optimization Method= 1
WQ AD Non Conservative
WQ ULTIMATE=-1
WQ Max Comp Step=1HOUR
WQ Output Interval=15MIN
WQ Output Selected Increments= 0
WQ Output face flow=0
WQ Output face velocity=0
WQ Output face area=0
WQ Output face dispersion=0
WQ Output cell volume=0
WQ Output cell surface area=0
WQ Output cell continuity=0
WQ Output cumulative cell continuity=0
WQ Output face conc=0
WQ Output face dconc_dx=0
WQ Output face courant=0
WQ Output face peclet=0
WQ Output face adv mass=0
WQ Output face disp mass=0
WQ Output cell mass=0
WQ Output cell source sink temp=0
WQ Output nsm pathways=0
WQ Output nsm derived pathways=0
WQ Create Restart=0
WQ Fixed Restart=0
WQ System Summary=0
WQ Write To DSS=0
Sorting and Armoring Iterations= 10
XS Update Threshold= 0.02
Bed Roughness Predictor= 0
Hydraulics Update Threshold= 0.02
Energy Slope Method= 1
Volume Change Method= 1
Sediment Retention Method= 0
Sediment TS Multiplier= 1
Warm Up Method= 0
XS Weighting Method= 0
Number of US Weighted Cross Sections= 1
Number of DS Weighted Cross Sections= 1
Upstream XS Weight=0
Main XS Weight=1
Downstream XS Weight=0
Number of DS XS's Weighted with US Boundary= 1
Upstream Boundary Weight= 1
Weight of XSs Associated with US Boundary= 0
Number of US XS's Weighted with DS Boundary= 1
Downstream Boundary Weight= 0.5
Weight of XSs Associated with DS Boundary= 0.5
Percentile Method= 0
Sediment Output Level= 3
Mass or Volume Output= 0
Output Increment Type= 1
Profile and TS Output Increment= 1
Transport Output Increment 1
XS Output Flag= 0
XS Output Increment= 10
Read HDF5 Sediment Hotstart= 0
Sediment Hotstart Type= 0
Write Gradation File= 0
Read Gradation Hotstart= 0
Write HDF5 File= 1
Write Binary Output= 1
Write DSS Sediment File= 0
DSS Sediment Output Type= 1
SV Curve= 0
Specific Gage Flag= 0
Subcell Erosion Methods= 0
Subcell Deposition Methods= 0
Advection Scheme= 1
Matrix Solver= 0
Implicit Weighting Factor= 1
Maximum Outer Loop Convergence Iterations= 5
Convergence Maximum Absolute= 0.001
Convergence RMSE= 0.0001
Grain Fractions Max Abs Error= 0.001
Max Subgrid Regions= 1
Max Subgrid Length Scale= 3.402823E+38
Initial Layer Thickness= 3.402823E+38
Min Layer Thickness= 3.402823E+38
Max Layer Thickness= 3.402823E+38
Number of Layers= 5

--- MARLNRN.f01 (steady flow) ---

Flow Title=Flow
Program Version=6.10
Number of Profiles= 6
Profile Names=01pct,10pct,04pct,02pct,0_2pct,01plus
River Rch & RM=MARLNRN,Main,5135
     268     137     185     225     380     396
River Rch & RM=MARLNRN,Main,4489
     325     168     226     274     459     481
River Rch & RM=MARLNRN,Main,2635
     407     212     284     344     573     602
Boundary for River Rch & Prof#=MARLNRN,Main            , 1
Up Type= 0
Dn Type= 3
Dn Slope=0.0074
Boundary for River Rch & Prof#=MARLNRN,Main            , 2
Up Type= 0
Dn Type= 3
Dn Slope=0.0074
Boundary for River Rch & Prof#=MARLNRN,Main            , 3
Up Type= 0
Dn Type= 3
Dn Slope=0.0074
Boundary for River Rch & Prof#=MARLNRN,Main            , 4
Up Type= 0
Dn Type= 3
Dn Slope=0.0074
Boundary for River Rch & Prof#=MARLNRN,Main            , 5
Up Type= 0
Dn Type= 3
Dn Slope=0.0074
Boundary for River Rch & Prof#=MARLNRN,Main            , 6
Up Type= 0
Dn Type= 3
Dn Slope=0.0074
DSS Import GetInterval= 0
DSS Import GetPeak= 0
DSS Import FillOption= 0

--- MARLNRN.g01 (geometry) ---

Geom Title=Geometry
Program Version=6.10

River Reach=MARLNRN         ,Main
Reach XY= 30
      2233502.64      445559.643     2233410.946      445709.238
     2233295.124      445779.276     2233246.952      445845.827
     2233121.825      445864.417     2232992.485      445825.342
      2232745.25      445669.695      2232289.04      445570.825
     2231948.311      445572.332     2231820.847      445596.975
     2231759.779      445559.414     2231475.961       445511.13
     2231293.219       445572.36     2231100.715      445699.738
     2231058.845      445702.003     2230833.114      445637.811
     2230763.314      445602.038     2230598.965      445596.141
     2230403.705      445564.547     2230187.133      445431.427
     2230085.585      445311.059     2229989.676       445368.48
     2229871.026      445395.437     2229806.267      445449.227
     2229776.179      445499.916      2229628.94      445605.622
     2229512.409      445608.101     2229249.799      445537.607
     2229146.565      445401.399     2228984.342      445298.064

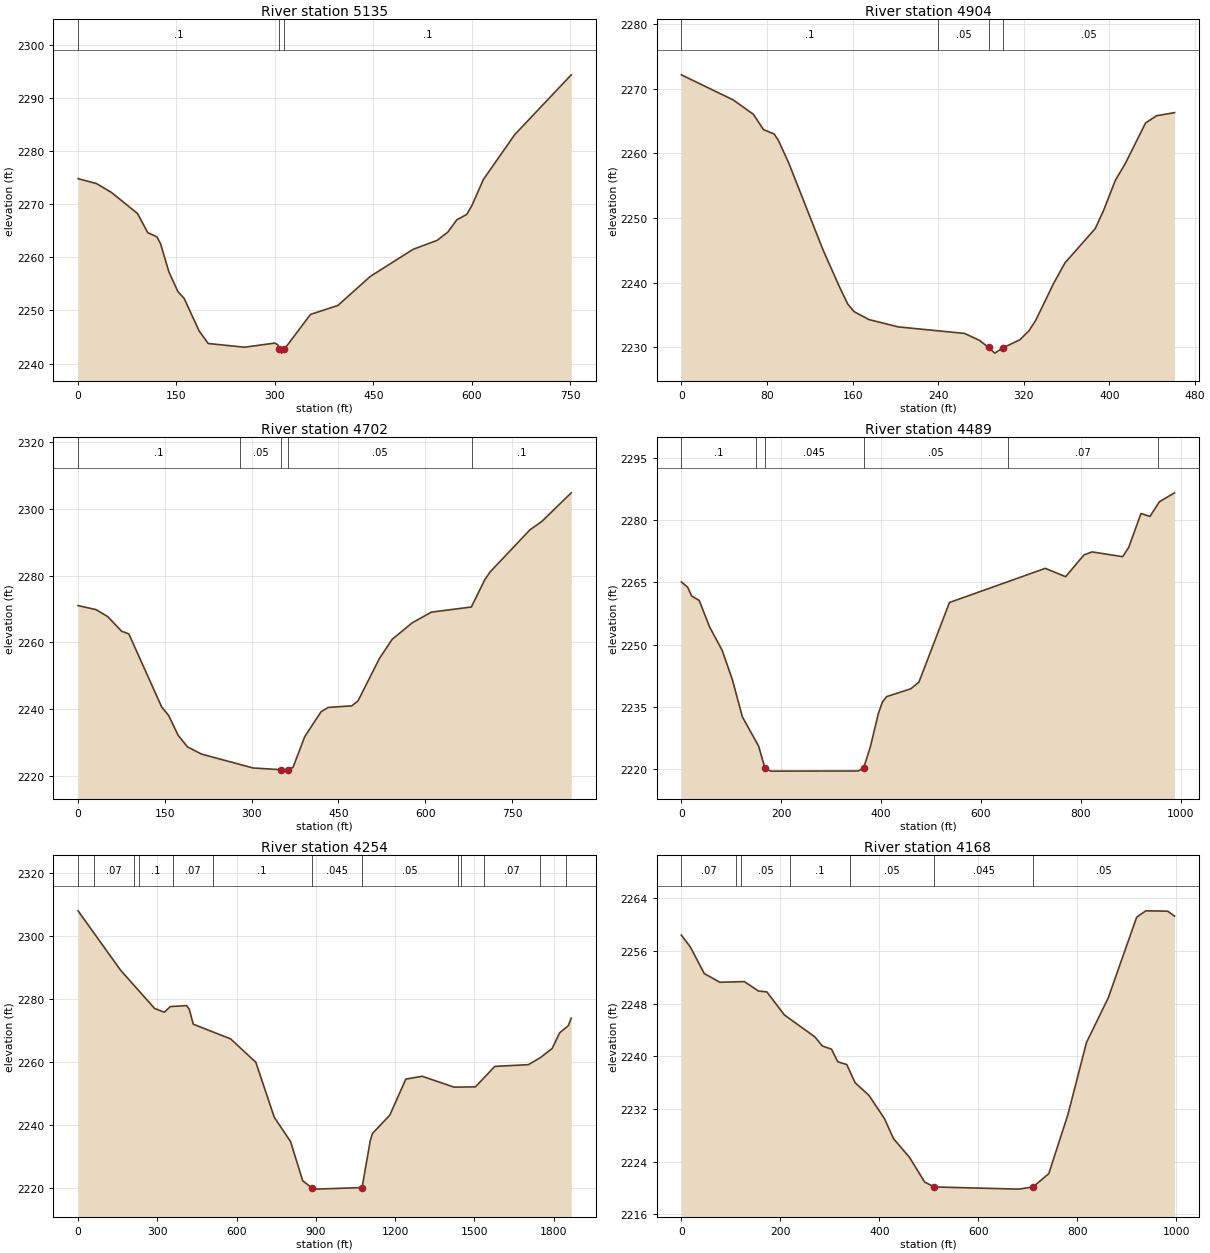
Type RM Length L Ch R = 1 ,5135    ,231.2,231.2,231.2
XS GIS Cut Line= 3
2233231.86641644445410.0431584322233575.69649604445606.277886787
2233924.55823534445535.834650967
#Sta/Elev= 30
       0 2274.79      28 2273.87      51 2272.19    90.5 2268.25   106.3 2264.63
   120.1 2263.86   125.7 2262.55   138.5 2257.23   152.3 2253.52   161.6 2252.28
   184.6 2246.14   198.4 2243.78   253.7 2243.08   299.7 2243.86   304.3 2243.56
  306.752242.724   310.4 2241.97   314.3  2242.7   354.4 2249.26   395.9 2250.92
   445.3 2256.38   510.6 2261.49   547.4 2263.19   563.7 2264.74   577.2 2267.03
   592.3 2268.05   600.4 2269.75   617.9 2274.64   665.7 2283.08   751.8 2294.32
#Mann= 3 ,-1,0
       0      .1       0  306.75    .045       0   314.3      .1       0
Bank Sta=306.75,314.3
XS Rating Curve= 0 ,0
Exp/Cntr(USF)=0,0
Exp/Cntr=0.3,0.1

Type RM Length L Ch R = 1 ,4904    ,201.8,201.8,201.8
XS GIS Cut Line= 2
2233206.70811794445483.840834052 2233448.2277836445876.310290762
#Sta/Elev= 30
       0 2272.17    48.5 2268.28    67.3 2266.06    76.7 2263.69    86.8    2263
    90.8 2261.97   100.2 2258.57   132.5 2245.01   147.8 2239.32   155.4  2236.7
   161.3 2235.52   175.3 2234.28   202.7 2233.15   264.6 2232.14   278.3 2231.09
     287 2229.97   292.8 2229.09   300.5 2229.91   316.3 2231.16   324.8 2232.56
     331 2234.14     348 2239.95   358.5 2243.08   386.7 2248.37   394.6 2251.22
   405.5 2255.85   414.9 2258.47   433.7 2264.71     444 2265.84   460.8 2266.32
#Mann= 4 ,-1,0
       0      .1       0     240     .05       0     287    .045       0
   300.5     .05       0
Bank Sta=287,300.5
XS Rating Curve= 0 ,0
Exp/Cntr(USF)=0,0
Exp/Cntr=0.3,0.1

Type RM Length L Ch R = 1 ,4702    ,212.9,212.9,212.9
XS GIS Cut Line= 2
2233154.71430102 445510.676352462233293.43634141446351.587014586
#Sta/Elev= 30
       0 2271.02    30.9 2269.82    51.2 2267.73    75.5 2263.31    87.7 2262.56
   144.4 2240.69   156.6 2238.09   172.8 2232.22     189 2228.73   213.3 2226.56
   302.5  2222.4350.99062221.879   355.2 2221.46362.79032221.929   371.5 2222.59
   391.7  2231.8   420.1 2239.27   432.3 2240.53   472.8    2241   483.7 2242.46
   520.7 2255.16   542.8 2260.92   577.6 2265.88   610.6 2269.06   679.6  2270.6
   702.9 2278.76     712 2281.08   780.9  2293.7   801.2 2296.18   852.3 2304.78
#Mann= 5 ,-1,0
       0      .1       0     280     .05       0350.9906    .045       0
362.7903     .05       0     680      .1       0
Bank Sta=350.9906,362.7903
XS Rating Curve= 0 ,0
Exp/Cntr(USF)=0,0
Exp/Cntr=0.3,0.1

Type RM Length L Ch R = 1 ,4489    ,235,235,235
XS GIS Cut Line= 3
2233057.43554679445540.8663106682232967.80097902446036.681005801
2233064.33609487446511.034592336
#Sta/Elev= 30
       0 2265.12    12.5 2263.88    20.6 2261.75    35.8 2260.66    56.4 2254.31
    81.6 2248.67   101.9 2241.66   122.3 2232.56   154.8 2225.52167.59752220.135
   179.2  2219.5     354 2219.54 364.8932220.211   378.3 2225.24   394.6 2233.41
   402.7 2236.17     411 2237.47   459.6 2239.36   475.9 2240.98     537 2260.17
   728.9 2268.41   769.7  2266.4   806.4 2271.65   822.8 2272.38     884 2271.23
   896.2  2273.5   920.7 2281.64   938.7 2280.95   957.5 2284.47   987.9 2286.63
#Mann= 6 ,-1,0
       0      .1       0     150    .025       0167.5975    .045       0
 364.893     .05       0  653.85     .07       0  953.85      .1       0
Bank Sta=167.5975,364.893
XS Rating Curve= 0 ,0
Exp/Cntr(USF)=0,0
Exp/Cntr=0.3,0.1

Type RM Length L Ch R = 1 ,4254    ,85.4,85.4,85.4
XS GIS Cut Line= 4
2233488.72199919445059.1210384412232827.65642043445621.372865891
2232761.41555891445903.5291218612232915.34386814446595.650997818
#Sta/Elev= 30
       0 2307.84   160.8 2289.01   289.5 2276.88   326.3 2275.66   348.9 2277.45
   410.7 2277.77   420.8 2276.62     436 2271.87   577.4  2267.2   672.9 2259.77
   742.5 2242.34   804.1 2234.66   850.3 2222.18   883.9    2220   900.5 2219.53
 1074.98 2220.03  1105.9 2234.87  1114.2 2237.18  1179.8 2242.99  1240.5 2254.44
  1302.8 2255.34  1422.8 2251.89    1504 2251.98  1577.3 2258.48  1704.3 2259.02
  1749.4 2261.23  1794.5 2264.17  1823.2 2269.17  1855.3 2271.37  1866.7 2273.78
#Mann= 13 ,-1,0
       0     .06       0      60     .07       0     210     .06       0
     230      .1       0     360     .07       0     510      .1       0
   883.9    .045       0 1074.98     .05       0 1437.66      .1       0
 1447.66     .05       0 1537.66     .07       0 1747.66     .05       0
 1847.66      .1       0
Bank Sta=883.9,1074.98
XS Rating Curve= 0 ,0
Exp/Cntr(USF)=0,0
Exp/Cntr=0.3,0.1

Type RM Length L Ch R = 1 ,4168    ,374.1,374.1,374.1
XS GIS Cut Line= 4
2232975.37868279445100.0451514612232749.48790583445539.913015069
2232713.58102449445799.2173406872232713.58102449446039.067889906
#Sta/Elev= 30
       0 2258.42    18.1 2256.61    46.2 2252.58    77.7 2251.25   127.2 2251.35
   155.9 2249.91   172.6 2249.79   208.1 2246.28   269.7 2242.94   284.6 2241.57
   303.3 2241.07     316 2239.15     334 2238.75   350.8 2235.99     379 2234.04
   410.2 2230.52   428.5 2227.47   460.7 2224.64   491.4 2220.87     511 2220.13
   681.2  2219.8     710 2220.12   742.1 2222.15   780.8 2231.15   818.2 2242.09
   862.2 2248.88   919.6 2261.14   938.2 2262.11   982.2 2262.06   996.1  2261.3
#Mann= 7 ,-1,0
       0     .07       0     110     .06       0     120     .05       0
     220      .1       0     340     .05       0     511    .045       0
     710     .05       0
Bank Sta=511,710
XS Rating Curve= 0 ,0
Exp/Cntr(USF)=0,0
Exp/Cntr=0.3,0.1

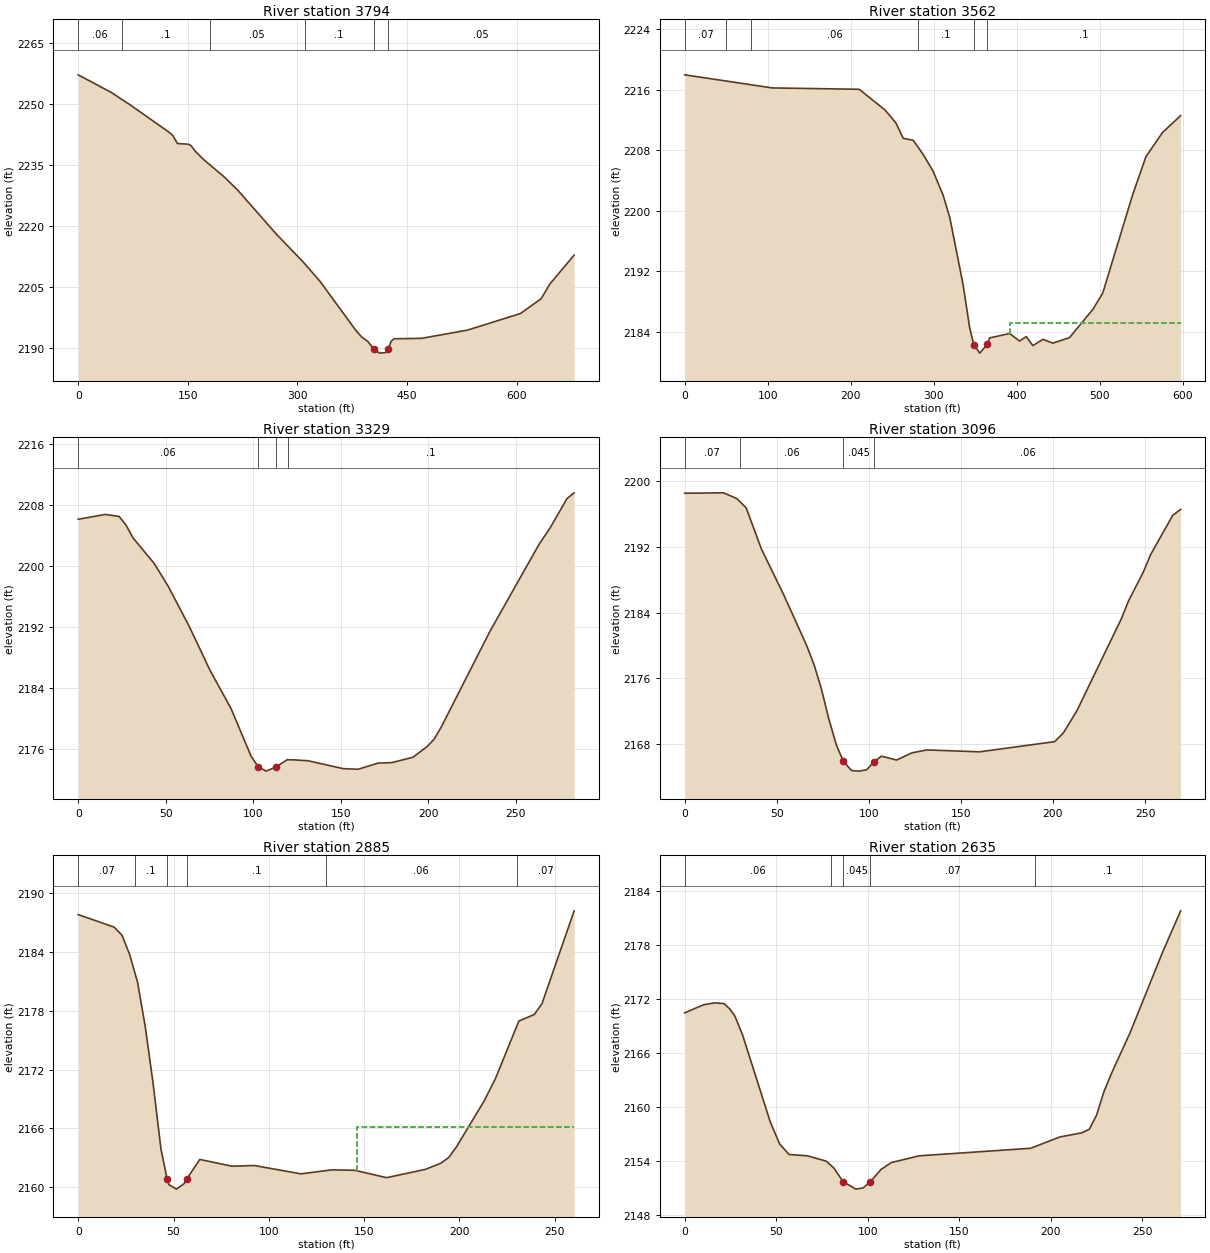
Type RM Length L Ch R = 1 ,3794    ,232.5,232.5,232.5
XS GIS Cut Line= 3
2232596.20007417445250.707267887 2232374.8070473 445510.67635246
2232339.58542939445846.120332554
#Sta/Elev= 30
       0 2257.12    45.3 2252.79    71.5 2249.69   123.8 2243.09   129.5  2242.2
   135.8 2240.24   150.4 2240.08   154.3 2239.75   160.4 2238.31     172 2236.25
   200.4 2231.96   218.7 2228.71   271.3 2217.96     308 2211.12   330.9 2206.39
   380.2 2194.29   388.2 2192.67   396.3 2191.62   404.2 2189.81   412.4 2188.74
   420.4 2188.84   424.4 2189.77   428.4 2191.67   432.5 2192.27   469.9 2192.37
     533  2194.4   605.4 2198.48   633.6  2202.1   645.6 2205.73   678.8 2212.83
#Mann= 6 ,-1,0
       0     .06       0      60      .1       0     180     .05       0
     310      .1       0   404.2    .045       0   424.4     .05       0
Bank Sta=404.2,424.4
XS Rating Curve= 0 ,0
Exp/Cntr(USF)=0,0
Exp/Cntr=0.3,0.1

Type RM Length L Ch R = 1 ,3562    ,233.3,233.3,233.3
XS GIS Cut Line= 3
2232272.49663338445252.3844877872232141.67348114445455.328095744
2232123.22406223445810.898714644
#Sta/Elev= 30
       0 2217.96   105.6 2216.23   210.3 2216.05   241.5  2213.3   254.5 2211.61
   263.3 2209.58   275.4 2209.31   287.4 2207.44   299.4 2205.21   311.4 2202.05
   319.4 2199.12   335.4 2190.27   343.4 2184.52  348.29 2182.34   355.5 2181.21
   364.3 2182.35   367.5 2183.22   391.5  2183.8   403.5  2182.8   411.5 2183.39
   419.5  2182.2   431.6 2183.03   443.6 2182.53   463.6 2183.25   492.2 2187.05
   503.7 2189.15   539.7 2202.12   555.7 2207.15   575.9 2210.37   597.5 2212.57
#Mann= 6 ,-1,0
       0     .07       0      50     .05       0      80     .06       0
  281.46      .1       0  348.29    .045       0   364.3      .1       0
#XS Ineff= 2 , 0
                          392.48         2185.14
Permanent Ineff=
       F       F
Bank Sta=348.29,364.3
XS Rating Curve= 0 ,0
Exp/Cntr(USF)=0,0
Exp/Cntr=0.3,0.1

Type RM Length L Ch R = 1 ,3329    ,232.4,232.4,232.4
XS GIS Cut Line= 2
2231901.83103537 445473.777514652231906.86269507445757.227677829
#Sta/Elev= 30
       0 2206.15    15.4 2206.78    23.4 2206.52    27.4 2205.35    31.4 2203.68
    43.4 2200.36    51.4 2197.37    63.4 2192.12    75.4 2186.29    87.4 2181.28
    98.8 2175.05   102.9 2173.65   107.4 2173.08  112.932173.613   119.4 2174.57
   123.4 2174.56   131.4 2174.44   151.4 2173.41   159.9 2173.32   171.4 2174.13
   179.4  2174.2   191.4 2174.91   199.4  2176.3   203.4 2177.26   207.4 2178.81
   235.4 2191.45   263.4 2202.84   269.9 2205.06   279.4 2208.87   283.5 2209.62
#Mann= 4 ,-1,0
       0     .06       0   102.9    .045       0  112.93     .06       0
     120      .1       0
Bank Sta=102.9,112.93
XS Rating Curve= 0 ,0
Exp/Cntr(USF)=0,0
Exp/Cntr=0.3,0.1

Type RM Length L Ch R = 1 ,3096    ,211.7,211.7,211.7
XS GIS Cut Line= 3
2231705.01879696445456.4809846222231663.08829945445657.747372679
2231664.76551935445721.481728897
#Sta/Elev= 30
       0 2198.53    21.1 2198.58    28.4 2197.87    33.4 2196.75    41.6 2191.78
    53.8 2186.15    66.1 2180.06    70.2 2177.69    74.3 2174.66    78.3 2171.02
    82.4 2167.85    86.22165.877    90.6 2164.76    94.7 2164.69    98.8 2164.85
   102.9 2165.85   106.9 2166.51   115.1 2166.04   123.3 2166.91   131.5 2167.27
   160.1 2167.04   200.9 2168.28   205.6 2169.33     213 2172.05     237 2183.19
     241 2185.41     249 2188.91     253 2191.05     265 2195.83   269.3 2196.57
#Mann= 4 ,-1,0
       0     .07       0      30     .06       0    86.2    .045       0
   102.9     .06       0
Bank Sta=86.2,102.9
XS Rating Curve= 0 ,0
Exp/Cntr(USF)=0,0
Exp/Cntr=0.3,0.1

Type RM Length L Ch R = 1 ,2885    ,249.5,249.5,249.5
XS GIS Cut Line= 2
2231467.43108115445458.6825355452231519.42489806445713.619960417
#Sta/Elev= 30
       0 2187.84    18.9 2186.55      23 2185.72      27 2183.75    31.1 2180.96
    35.2 2176.37    39.3 2170.58    43.4 2163.93   46.61 2160.89    47.5 2160.28
    51.5 2159.81    55.6 2160.38      57 2160.86    63.8 2162.84    80.7 2162.15
    92.4 2162.22   116.9 2161.37   133.2 2161.78   145.2 2161.73   161.8 2160.98
   182.2 2161.83   190.3 2162.46   194.4 2163.04   198.5 2164.14     213 2168.82
   218.9 2171.09   231.2 2176.97   239.3 2177.64   243.3 2178.73   260.2 2188.22
#Mann= 6 ,-1,0
       0     .07       0      30      .1       0   46.61    .045       0
      57      .1       0     130     .06       0     230     .07       0
#XS Ineff= 2 , 0
                          146.01         2166.18
Permanent Ineff=
       F       F
Bank Sta=46.61,57
XS Rating Curve= 0 ,0
Exp/Cntr(USF)=0,0
Exp/Cntr=0.3,0.1

Type RM Length L Ch R = 1 ,2635    ,45.9,45.9,45.9
BEGIN DESCRIPTION:
Structure XS 4
END DESCRIPTION:
XS GIS Cut Line= 3
2231190.68038455445524.2628801792231283.92515685445643.824121315
2231287.17410362445763.060467775
#Sta/Elev= 30
       0 2170.48    10.3 2171.38    16.4 2171.59    21.5 2171.51    24.5 2170.95
    27.4 2170.14    31.6 2168.04    46.8 2158.33    51.9  2155.9      57 2154.74
    67.1 2154.59    77.3    2154    81.5 2153.24    86.52151.723    93.5 2150.89
    97.5 2151.03   101.5 2151.72   107.2 2153.07   112.9 2153.84     128 2154.59
     189 2155.43     205 2156.69     217 2157.15     221 2157.54     225 2159.11
     229 2161.71     233 2163.69   243.3 2168.27     261  2177.2   270.9 2181.82
#Mann= 5 ,-1,0
       0     .06       0      80     .07       0    86.5    .045       0
   101.5     .07       0  191.62      .1       0
Bank Sta=86.5,101.5
XS Rating Curve= 0 ,0
Exp/Cntr(USF)=0,0
Exp/Cntr=0.5,0.3

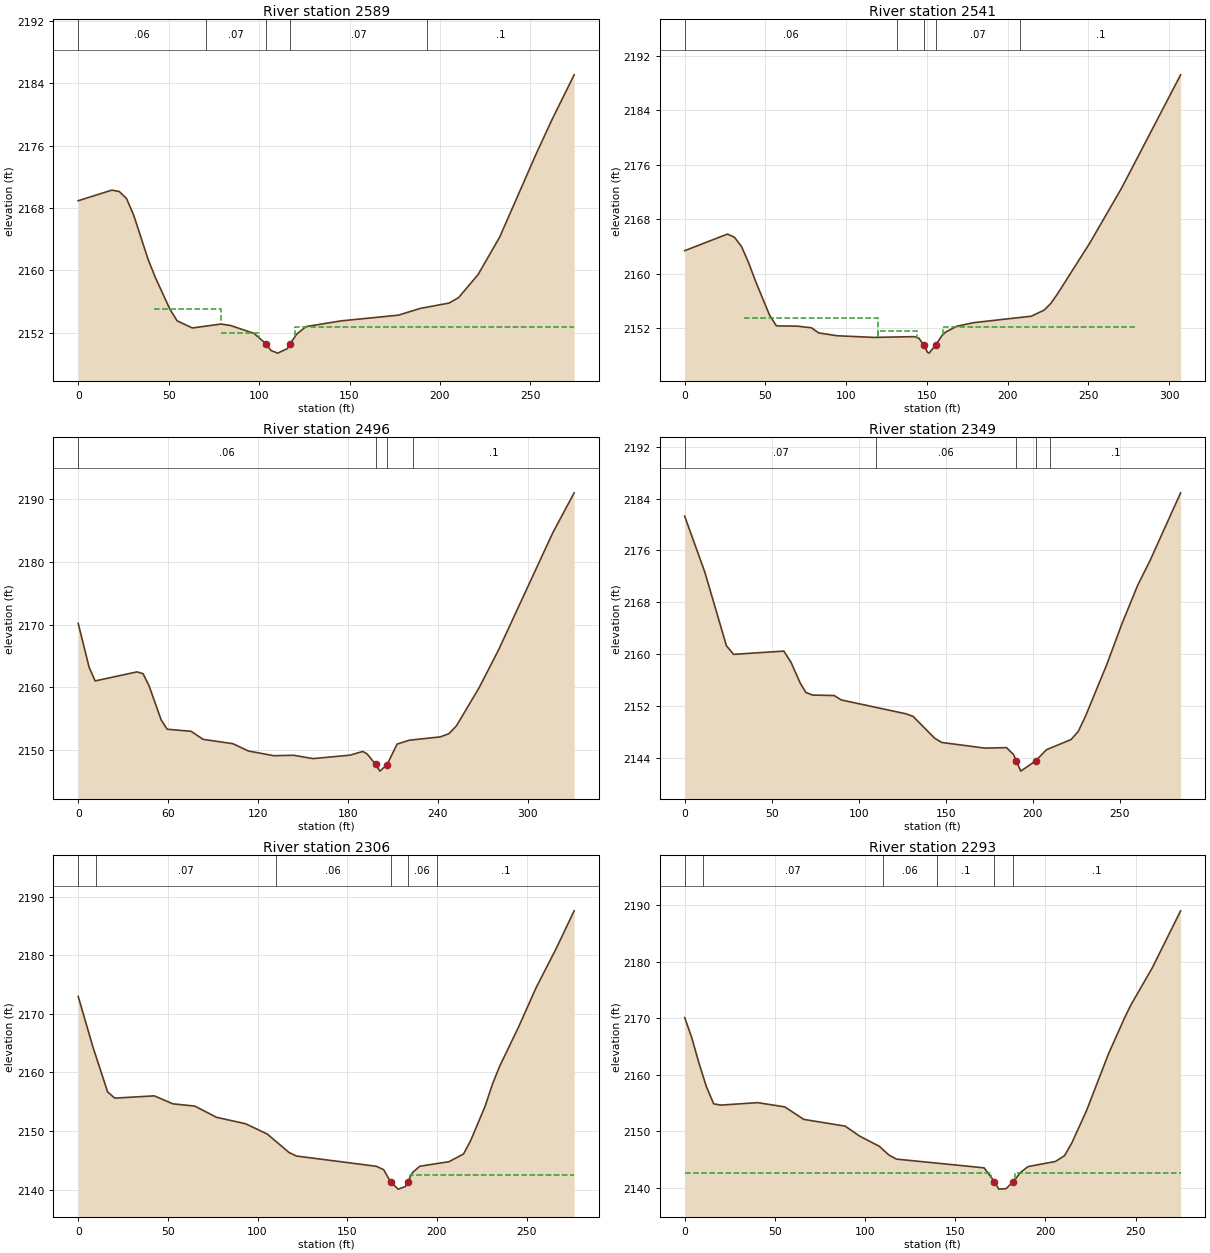
Type RM Length L Ch R = 1 ,2589    ,47.9,47.9,47.9
BEGIN DESCRIPTION:
Structure XS 3; 3.4 ft between structure and xs
END DESCRIPTION:
XS GIS Cut Line= 4
2231172.20054962445521.2254780272231176.44919207445581.717899367
2231248.56981404445667.8899471262231255.39260225445768.820872784
#Sta/Elev= 30
       0 2168.94    18.6  2170.3    22.7 2170.12    26.7 2169.23    30.7 2167.07
    38.7 2161.38    42.7 2159.07    50.7 2155.03    54.7 2153.53    63.1 2152.62
      79 2153.12    84.3 2152.93    97.2 2151.92  103.77  2150.6   106.5 2149.74
   110.3 2149.39   115.6 2149.96   117.1 2150.56   120.8 2151.83     126  2152.8
   145.5 2153.53     177 2154.26   189.2 2155.13     205 2155.81   210.3 2156.51
   221.1 2159.47   233.1 2164.31     253 2174.85   261.8 2179.27   274.2 2185.09
#Mann= 5 ,-1,0
       0     .06       0   70.64     .07       0  103.77    .045       0
   117.1     .07       0  193.01      .1       0
#XS Ineff= 4 ,-1
       0   41.92    2152   41.92   78.93 2155.02   78.93     100    2152
     120   274.2  2152.8
Permanent Ineff=
       F       F       F       F
Bank Sta=103.77,117.1
XS Rating Curve= 0 ,0
Exp/Cntr(USF)=0,0
Exp/Cntr=0.5,0.3

Type RM Length L Ch R = 1 ,2541    ,44.8,44.8,44.8
BEGIN DESCRIPTION:
Structure XS 2; 13 ft between structure and xs
END DESCRIPTION:
XS GIS Cut Line= 4
2231087.84784466445520.7310937122231119.18371521445595.726807052
2231207.55742324445686.2804575382231202.68400309 445785.58690981
#Sta/Elev= 30
       0 2163.35    26.5 2165.79    30.8 2165.33    35.2 2163.97    39.5 2161.64
    43.8 2158.93    52.5 2153.93    56.8 2152.31    69.8 2152.27    78.5 2152.03
      83 2151.28    94.5 2150.86   117.1 2150.62   142.4 2150.73   145.2 2150.48
   148.1 2149.48   150.4 2148.43   151.4 2148.31   155.4 2149.49   159.4 2150.89
   161.6 2151.39   168.6 2152.26   179.2 2152.79   214.7 2153.73   222.7 2154.63
   226.7 2155.58   230.7 2156.92   250.8 2164.42   270.5 2172.48   307.2 2189.17
#Mann= 5 ,-1,0
       0     .06       0  131.28     .07       0   148.1    .045       0
   155.4     .07       0  207.81      .1       0
#XS Ineff= 4 ,-1
       0   36.87    2152   36.87     120 2153.54     120     144  2151.6
     160   278.9  2152.1
Permanent Ineff=
       F       F       F       F
Bank Sta=148.1,155.4
XS Rating Curve= 0 ,0
Exp/Cntr(USF)=0,0
Exp/Cntr=0.5,0.3

Type RM Length L Ch R = 1 ,2496    ,147.7,147.7,147.7
BEGIN DESCRIPTION:
Structure XS 1
END DESCRIPTION:
XS GIS Cut Line= 4
2231055.68473174445501.9139737382231061.67649876445605.025162273
 2231167.9348333445707.5829090872231174.10783216 445787.50699963
#Sta/Elev= 30
       0 2170.18     7.3  2163.2    11.3 2161.04    39.3 2162.48    43.3 2162.19
    47.3 2160.27    55.4 2154.83    59.4 2153.36    75.4 2153.03    83.4 2151.75
   103.3 2151.06   113.6  2149.9   130.6 2149.15   143.8 2149.22   156.8 2148.69
   181.5 2149.24     190 2149.83   192.9 2149.43198.60052147.762   201.4  2146.7
206.19032147.742   212.9    2151   221.1 2151.62   241.7 2152.14   247.5 2152.65
   252.6 2153.93   267.6 2159.94   280.6 2165.95   316.8 2184.57   331.1 2190.94
#Mann= 4 ,-1,0
       0     .06       0198.6005    .045       0206.1903     .06       0
  223.29      .1       0
Bank Sta=198.6005,206.1903
XS Rating Curve= 0 ,0
Exp/Cntr(USF)=0,0
Exp/Cntr=0.3,0.1

Type RM Length L Ch R = 1 ,2349    ,42.9,42.9,42.9
BEGIN DESCRIPTION:
Structure XS 4
END DESCRIPTION:
XS GIS Cut Line= 2
2231049.68535028445485.9322769522230979.36825817445762.248737501
#Sta/Elev= 30
       0 2181.29    11.6 2172.65      24 2161.31    28.1 2159.98      57 2160.48
    61.1 2158.77    66.4 2155.56    69.7  2154.1    73.5  2153.7    85.9 2153.63
      90 2152.95   127.2 2150.81   131.3 2150.42   143.7 2147.05   147.8 2146.39
   172.6 2145.52     185 2145.59   189.1 2144.52   190.6 2143.56   193.2 2141.97
   201.7 2143.54   207.9 2145.26   222.1 2146.84   226.2 2148.07   230.4 2150.43
   242.7 2158.44   251.5 2164.79   260.5 2170.68   267.5 2174.43   285.1 2184.89
#Mann= 5 ,-1,0
       0     .07       0     110     .06       0   190.6    .045       0
   201.7     .06       0     210      .1       0
Bank Sta=190.6,201.7
XS Rating Curve= 0 ,0
Exp/Cntr(USF)=0,0
Exp/Cntr=0.5,0.3

Type RM Length L Ch R = 1 ,2306    ,13.1,13.1,13.1
BEGIN DESCRIPTION:
Structure XS 3; 6.8 ft between structure and XS
END DESCRIPTION:
XS GIS Cut Line= 2
2230988.37614742445484.9760365492230945.55588412445758.127877476
#Sta/Elev= 30
       0 2172.95     8.3 2164.24    16.4 2156.66    20.4  2155.6    42.4 2155.99
    52.8 2154.63      65 2154.24    77.1 2152.33    93.3 2151.23   105.4 2149.47
   117.6 2146.31   121.7 2145.72   166.2 2143.97   170.3 2143.39   174.3 2141.24
   178.4 2140.07   182.4 2140.51  183.632141.248   186.5 2142.94   190.5 2143.98
   206.7 2144.75   214.8 2146.06   218.8 2148.35   226.9 2154.25     231 2158.03
     235 2161.07   245.4 2167.67   255.3 2174.46   266.4 2181.08   276.5 2187.57
#Mann= 6 ,-1,0
       0     .06       0      10     .07       0     110     .06       0
   174.3    .045       0  183.63     .06       0     200      .1       0
#XS Ineff= 2 , 0
             172  2142.4     185          2142.4
Permanent Ineff=
       F       F
Bank Sta=174.3,183.63
XS Rating Curve= 0 ,0
Exp/Cntr(USF)=0,0
Exp/Cntr=0.5,0.3

Type RM Length L Ch R = 1 ,2293    ,85.4,85.4,85.4
BEGIN DESCRIPTION:
Structure XS 2; 3.2 ft between structure and XS
END DESCRIPTION:
XS GIS Cut Line= 2
2230975.94445807445485.3213612532230932.08822066 445756.74657866
#Sta/Elev= 30
       0 2170.12     3.9 2166.59       8 2161.98      12 2157.91    16.1 2154.83
    20.1 2154.61    40.4 2155.05    55.5 2154.29      66 2152.08      89 2150.88
    97.1 2149.09   107.8 2147.33   113.3 2145.74   117.4 2145.04     166 2143.49
  171.642141.069   174.1 2139.72   178.1  2139.8   182.2 2141.05   186.2 2142.69
   190.3 2143.71   205.5 2144.62   210.6 2145.66   214.6 2147.91   222.7  2153.6
   234.9 2163.68   243.9 2170.12   247.3 2172.33   259.2 2178.95   274.9 2189.04
#Mann= 6 ,-1,0
       0     .06       0      10     .07       0     110     .06       0
     140      .1       0  171.64    .045       0   182.2      .1       0
#XS Ineff= 2 , 0
             170  2142.5   183.3          2142.5
Permanent Ineff=
       F       F
Bank Sta=171.64,182.2
XS Rating Curve= 0 ,0
Exp/Cntr(USF)=0,0
Exp/Cntr=0.5,0.3

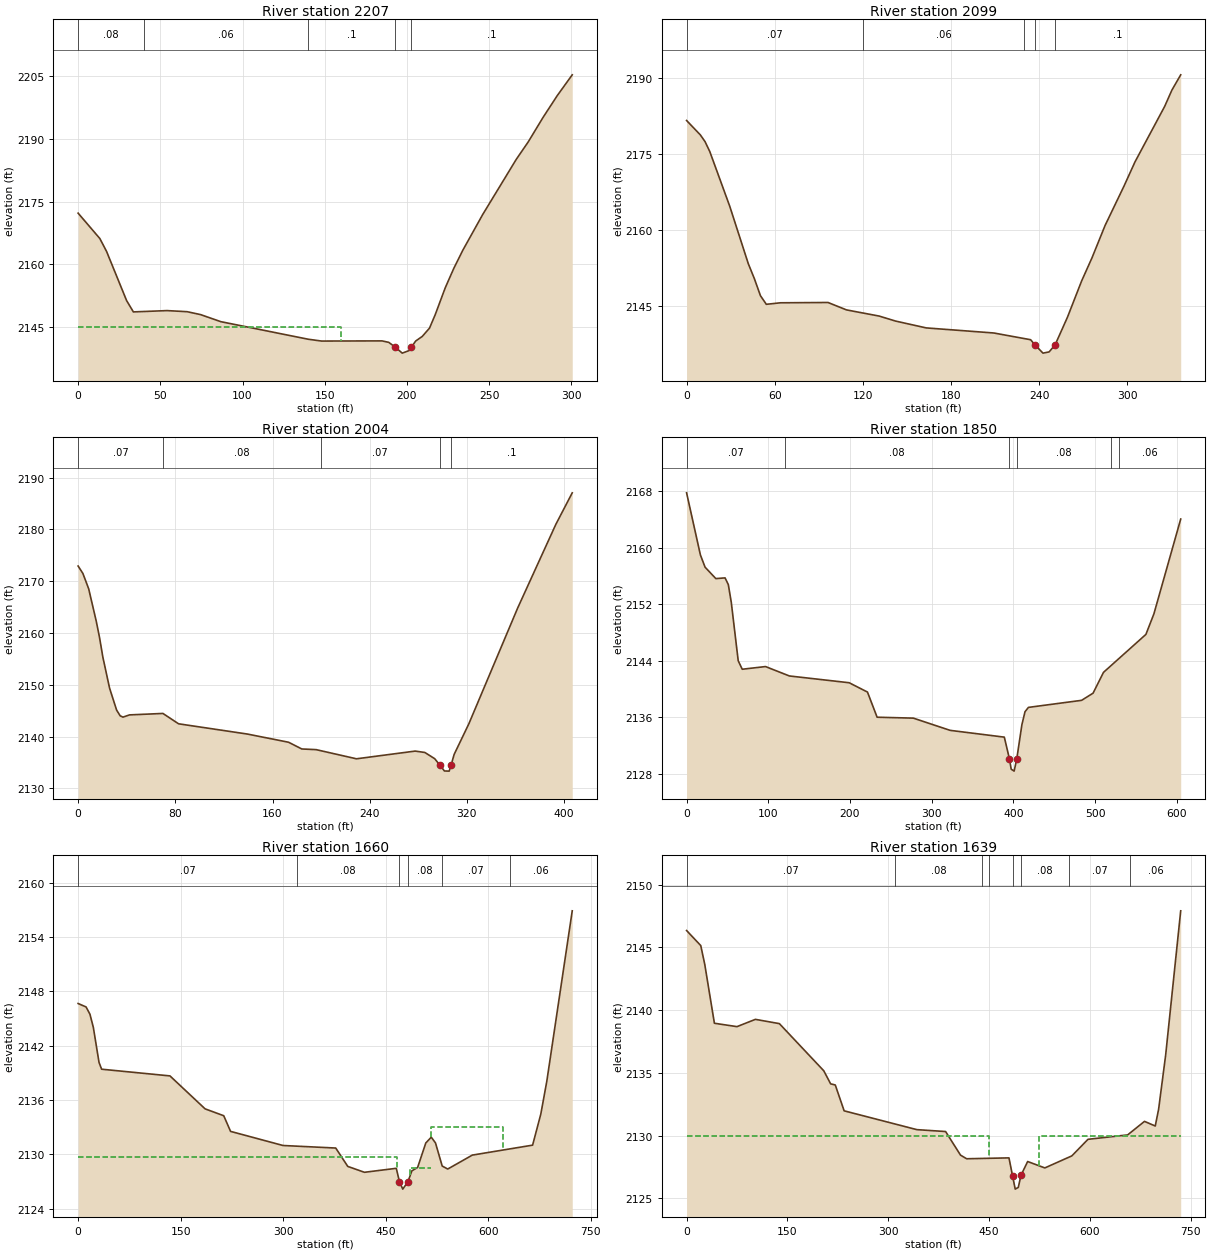
Type RM Length L Ch R = 1 ,2207    ,107.9,107.9,107.9
BEGIN DESCRIPTION:
Structure XS 1
END DESCRIPTION:
XS GIS Cut Line= 2
2230904.09925817445452.2593032652230842.69560027445746.402632236
#Sta/Elev= 30
       0 2172.23    13.2 2166.16    17.3 2163.07    29.5 2151.29    33.6 2148.59
    54.1  2148.9    66.3 2148.64    74.5 2147.94    86.8 2146.25   139.9 2142.05
     148 2141.61   184.8 2141.65   188.9  2141.3     193 2140.12   197.1 2138.72
   201.2 2139.31   202.7 2140.17   205.3 2141.62   209.3 2142.72   213.7 2144.71
   217.1 2147.86   223.3 2154.39   228.5 2159.04     234 2163.39   246.1 2171.94
   266.5 2185.14   273.7 2189.27   282.9 2195.25   291.4 2200.38   300.5 2205.35
#Mann= 5 ,-1,0
       0     .08       0      40     .06       0     140      .1       0
     193    .045       0   202.7      .1       0
#XS Ineff= 2 , 0
             160    2145
Permanent Ineff=
       F       F
Bank Sta=193,202.7
XS Rating Curve= 0 ,0
Exp/Cntr(USF)=0,0
Exp/Cntr=0.3,0.1

Type RM Length L Ch R = 1 ,2099    ,95,95,95
XS GIS Cut Line= 2
2230835.76292921445373.0287769422230737.71515289445694.902790127
#Sta/Elev= 30
       0 2181.57     9.4 2178.72    12.6 2177.39    15.8 2175.45    29.4 2164.66
      42 2153.37    46.2 2150.37    50.3 2147.04    54.3 2145.34    63.9 2145.64
    96.3  2145.7   108.9 2144.24   131.2 2143.02   142.3 2142.04   163.2 2140.69
   209.2 2139.69   234.3 2138.36  237.052137.404   242.7 2135.72   246.9 2135.96
     251 2137.37   259.4 2142.81     269 2149.93   276.1 2154.51     285 2160.88
   297.9 2168.65   305.4 2173.43   325.6 2184.36   330.5 2187.56   336.5 2190.57
#Mann= 5 ,-1,0
       0     .07       0     120     .06       0     230      .1       0
  237.05    .045       0     251      .1       0
Bank Sta=237.05,251
XS Rating Curve= 0 ,0
Exp/Cntr(USF)=0,0
Exp/Cntr=0.3,0.1

Type RM Length L Ch R = 1 ,2004    ,154.1,154.1,154.1
BEGIN DESCRIPTION:
Structure XS 4
END DESCRIPTION:
XS GIS Cut Line= 3
2230807.04186342 445355.201908522230661.45577131445491.874566426
2230682.25378447445697.873934864
#Sta/Elev= 30
       0 2172.93     3.9 2171.51     8.7 2168.53    14.9  2162.3    17.6 2159.16
    20.4 2155.29    25.9 2149.34    31.7  2145.1    34.6 2144.01    36.9 2143.75
    42.3 2144.18    69.8 2144.46    82.7 2142.46   139.3 2140.48   173.2  2138.9
   184.1  2137.6   195.9 2137.47   229.1  2135.7   277.4 2137.19   285.4 2136.92
   293.5 2135.72   297.5 2134.56   301.5 2133.35   305.4 2133.32  307.072134.542
   309.5 2136.55   321.6 2142.46   361.8 2164.83   393.2 2180.98   406.7 2187.07
#Mann= 5 ,-1,0
       0     .07       0      70     .08       0  199.69     .07       0
   297.5    .045       0  307.07      .1       0
Bank Sta=297.5,307.07
XS Rating Curve= 0 ,0
Exp/Cntr(USF)=0,0
Exp/Cntr=0.5,0.3

Type RM Length L Ch R = 1 ,1850    ,190.6,190.6,190.6
BEGIN DESCRIPTION:
Structure XS 3; 15.7 ft between structure and xs
END DESCRIPTION:
XS GIS Cut Line= 5
2230804.07071869 445303.702066412230556.47532393445554.268605905
2230523.76583765445568.1123406192230513.76557949445598.113115093
2230418.81228444445757.296829606
#Sta/Elev= 30
       0 2167.75    16.9 2158.97    22.6 2157.23    35.8 2155.61    47.1 2155.71
    51.1 2154.76    54.7 2152.26    63.2 2143.98    68.1 2142.78    96.6 2143.16
   125.8 2141.83     199 2140.87   221.4 2139.55   233.2 2135.99   277.6 2135.86
   322.6 2134.13   388.9 2133.17  395.23 2130.06   397.3 2128.64   400.9 2128.36
   404.1 2130.05   410.4 2134.92   414.2 2136.76   418.4 2137.38   483.5 2138.38
   497.5 2139.39   510.3 2142.34   562.2 2147.71     572 2150.62   604.8 2164.04
#Mann= 6 ,-1,0
       0     .07       0     120     .08       0  395.23    .045       0
   404.1     .08       0   519.4      .1       0   529.4     .06       0
#XS Ineff= 2 , 0
             380  2133.1     420          2130.7
Permanent Ineff=
       F       F
Bank Sta=395.23,404.1
XS Rating Curve= 0 ,0
Exp/Cntr(USF)=0,0
Exp/Cntr=0.5,0.3

Type RM Length L Ch R = 1 ,1660    ,20.3,20.3,20.3
BEGIN DESCRIPTION:
Structure XS 2; 10.1 ft between structure and xs
END DESCRIPTION:
XS GIS Cut Line= 4
2230713.92783536445238.6763800482230344.28752018445519.163708582
2230332.18194452445544.4275186662230318.78374496445775.123698028
#Sta/Elev= 30
       0 2146.66    11.6 2146.28    17.3 2145.48    22.3 2144.01    30.6 2140.15
    34.4  2139.4   134.4 2138.66   185.8 2135.02   213.1 2134.26   223.1 2132.53
   299.9 2130.97     377 2130.69   394.6 2128.66     419 2128.01   465.6 2128.45
  470.252126.975   475.1 2126.15   482.8 2126.99   488.4 2128.17   496.8 2128.54
   508.8 2131.25   516.8 2131.89     523 2131.25   532.8  2128.7   540.9 2128.37
   576.9 2129.91   665.1 2131.01   677.1 2134.44   685.9 2138.08   723.1  2156.9
#Mann= 6 ,-1,0
       0     .07       0     320     .08       0  470.25    .045       0
   482.8     .08       0  532.03     .07       0  632.03     .06       0
#XS Ineff= 4 ,-1
       0     466  2129.7     486  516.51  2128.5  516.51  621.97 2133.06
  621.97   723.1  2129.5
Permanent Ineff=
       F       F       F       F
Bank Sta=470.25,482.8
XS Rating Curve= 0 ,0
Exp/Cntr(USF)=0,0
Exp/Cntr=0.5,0.3

Type RM Length L Ch R = 1 ,1639    ,26.4,26.4,26.4
BEGIN DESCRIPTION:
Structure XS 4/1
END DESCRIPTION:
XS GIS Cut Line= 4
2230704.72764275445212.4601677732230328.45855112445508.100168338
2230307.46849165445543.7053739962230316.60974067445759.096054043
#Sta/Elev= 30
       0 2146.35    21.1 2145.15    27.1 2143.64    41.4 2138.96      75 2138.69
   102.4 2139.27   138.1 2138.93   204.2 2135.17   214.4 2134.13   221.3 2134.04
   234.5 2131.98   342.8 2130.48   385.5 2130.33   407.7 2128.45   416.8 2128.16
   479.8 2128.23   485.3 2126.76   489.1 2125.74   493.7 2125.88   497.72126.843
   507.6 2127.94   533.2 2127.43   573.4 2128.39   597.4 2129.71   656.4 2130.06
   681.5 2131.14   697.5 2130.77   702.5  2132.1     713 2136.42   735.4 2147.92
#Mann= 8 ,-1,0
       0     .07       0     310     .08       0     440     .07       0
     450     .08       0   485.3    .045       0   497.7     .08       0
  569.85     .07       0  659.85     .06       0
#XS Ineff= 2 , 0
             450    2130     525            2130
Permanent Ineff=
       F       F
Bank Sta=485.3,497.7
XS Rating Curve= 0 ,0
Exp/Cntr(USF)=0,0
Exp/Cntr=0.5,0.3