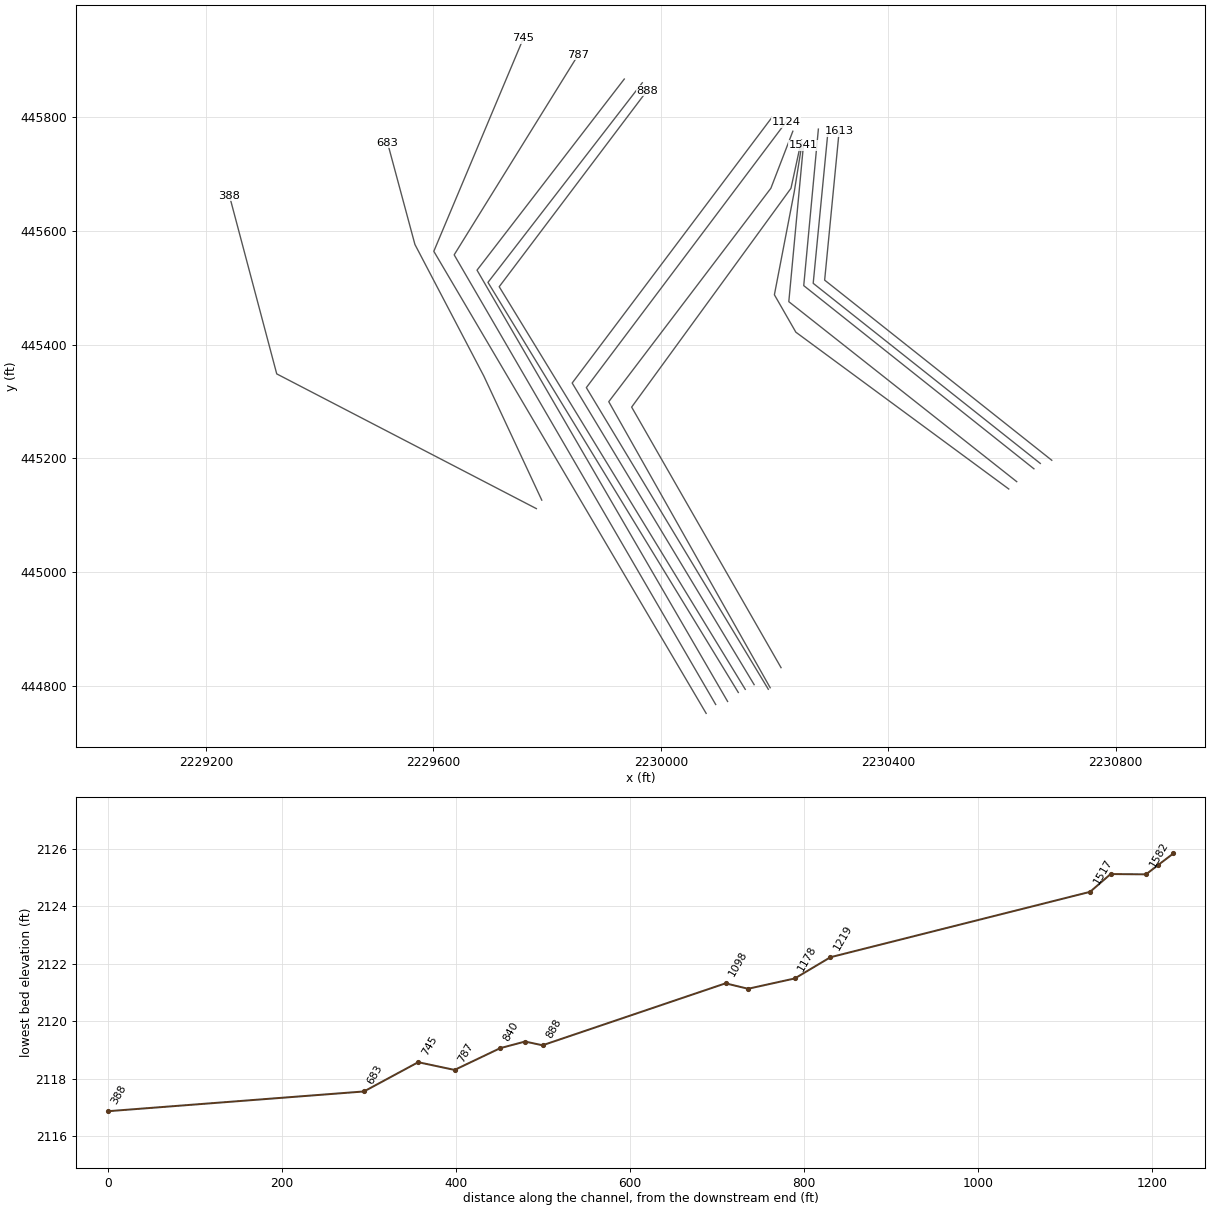
HEC-RAS study MARLNRN.prj: MARLNRN

--- MARLNRN.g01 (geometry) --- (continued)

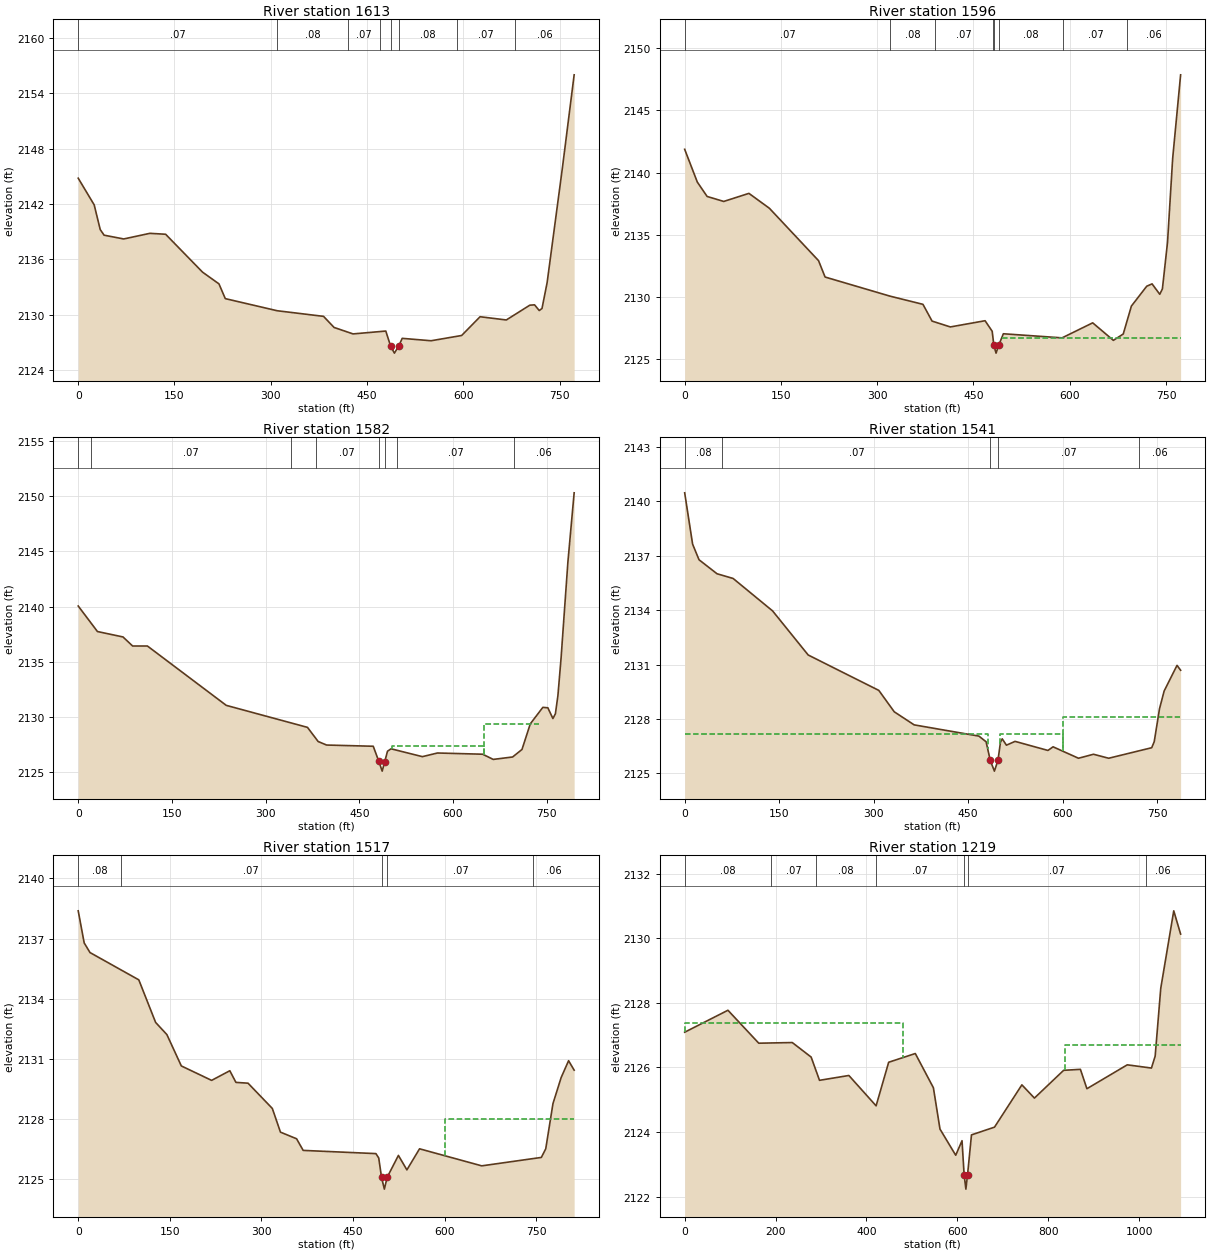
Type RM Length L Ch R = 1 ,1613    ,17.4,17.4,17.4
BEGIN DESCRIPTION:
Structure XS 3; 9.1 ft between structure and xs
END DESCRIPTION:
XS GIS Cut Line= 3
2230687.71638149445196.5638304452230288.21626014445513.436416655
2230313.69902271445775.090461331
#Sta/Elev= 30
       0 2144.79    24.9  2141.9    34.3 2139.23    40.3 2138.62    70.9 2138.21
   111.7 2138.82   136.2 2138.72   193.7 2134.62   219.3 2133.35   229.2 2131.75
     310 2130.44   382.3 2129.83   398.7 2128.63   428.3 2127.93   479.3 2128.24
     487 2126.57   492.7 2125.85  499.212126.588   504.9 2127.45   549.9 2127.19
   597.5 2127.76   626.2 2129.79   667.1 2129.44   703.7 2131.04   711.1 2131.08
   718.4 2130.46   722.7 2130.68   730.7 2133.49   754.6 2145.96   772.8 2155.98
#Mann= 8 ,-1,0
       0     .07       0     310     .08       0     420     .07       0
     470     .08       0     487    .045       0  499.21     .08       0
  589.91     .07       0  679.91     .06       0
#XS Ineff= 2 , 0
             479  2126.8     508          2126.7
Permanent Ineff=
       F       F
Bank Sta=487,499.21
XS Rating Curve= 0 ,0
Exp/Cntr(USF)=0,0
Exp/Cntr=0.5,0.3

Type RM Length L Ch R = 1 ,1596    ,14.1,14.1,14.1
BEGIN DESCRIPTION:
Structure XS 2; 5 ft between structure and xs
END DESCRIPTION:
XS GIS Cut Line= 3
2230667.57544372445190.9653623292230268.07532237445507.837948539
2230293.55808493445769.491993215
#Sta/Elev= 30
       0 2141.87    19.7 2139.23      35 2138.07    60.9 2137.67   100.1 2138.32
     132 2137.12   208.6  2132.9   218.8 2131.58     320 2130.04   371.3 2129.38
   385.5 2128.03     414 2127.56   468.1 2128.06   479.2 2127.21  481.782126.078
   485.2 2125.45   489.4 2126.09   496.6 2127.01   588.1 2126.68   635.8 2127.89
     668 2126.48   683.4 2126.99   696.1 2129.24     720 2130.84   728.3 2131.03
   740.3 2130.19   744.4 2130.62   752.4 2134.38   760.4 2141.13   772.8 2147.87
#Mann= 8 ,-1,0
       0     .07       0     320     .08       0     390     .07       0
     480     .08       0  481.78    .045       0   489.4     .08       0
  589.91     .07       0  689.91     .06       0
#XS Ineff= 2 , 0
             476  2126.8     494          2126.7
Permanent Ineff=
       F       F
Bank Sta=481.78,489.4
XS Rating Curve= 0 ,0
Exp/Cntr(USF)=0,0
Exp/Cntr=0.5,0.3

Type RM Length L Ch R = 1 ,1582    ,40.7,40.7,40.7
BEGIN DESCRIPTION:
Structure XS 3; 12.8 ft between structure and xs
END DESCRIPTION:
XS GIS Cut Line= 3
2230656.30578709445181.5880177162230251.43779759445503.759145374
2230277.18771864445779.085224344
#Sta/Elev= 30
       0 2140.06    30.8 2137.75    71.7 2137.26    87.1 2136.44   110.8 2136.44
     237 2131.07     367 2129.08   384.1  2127.8   397.6 2127.48   472.3 2127.37
   481.1 2126.02   486.6 2125.12  490.752125.988   495.1 2126.92   500.8 2127.14
     551 2126.43   575.1 2126.76   647.4 2126.65   664.4 2126.18   695.4  2126.4
   710.4 2127.08   723.7  2129.4   743.8 2130.89   751.8 2130.85   759.9 2129.88
   763.9 2130.31   767.9 2131.95   772.9  2135.3   783.9 2144.05   793.9  2150.3
#Mann= 8 ,-1,0
       0     .08       0      20     .07       0     340     .08       0
     380     .07       0   481.1    .045       0  490.75     .08       0
     510     .07       0  697.41     .06       0
#XS Ineff= 4 ,-1
       0     469 2127.36     503     650 2127.38     650  737.77 2129.35
  737.77   793.9 2127.38
Permanent Ineff=
       F       F       F       F
Bank Sta=481.1,490.75
XS Rating Curve= 0 ,0
Exp/Cntr(USF)=0,0
Exp/Cntr=0.5,0.3

Type RM Length L Ch R = 1 ,1541    ,23.6,23.6,23.6
BEGIN DESCRIPTION:
Structure XS 2; 8.6 ft between structure and xs
END DESCRIPTION:
XS GIS Cut Line= 3
2230626.04962986445158.9776062672230225.19268574445475.533270372
 2230250.9426068445750.859349342
#Sta/Elev= 30
       0 2140.47    12.6 2137.64    22.8 2136.78    51.3 2136.01    76.9 2135.75
   139.6 2133.96   196.1 2131.53   308.2 2129.58   332.7  2128.4   364.3 2127.68
   467.1 2127.06   478.5 2126.75  485.12 2125.72   491.7 2125.13  497.33 2125.72
   501.3 2126.72   504.1 2126.91   510.8 2126.56   524.5 2126.77   576.7 2126.27
   584.8 2126.47   625.2 2125.84     649 2126.06   673.1 2125.84   741.4 2126.42
   745.4 2126.75   753.8 2128.57   761.2 2129.55   781.6 2130.96   787.3 2130.69
#Mann= 5 ,-1,0
       0     .08       0      60     .07       0  485.12    .045       0
  497.33     .07       0  720.78     .06       0
#XS Ineff= 3 ,-1
       0     481  2127.2     501     600  2127.2     600  785.61 2128.14
Permanent Ineff=
       F       F       F
Bank Sta=485.12,497.33
XS Rating Curve= 0 ,0
Exp/Cntr(USF)=0,0
Exp/Cntr=0.5,0.3

Type RM Length L Ch R = 1 ,1517    ,298.4,298.4,298.4
BEGIN DESCRIPTION:
Structure XS 1
END DESCRIPTION:
XS GIS Cut Line= 5
2230612.05313428445146.0546922782230237.57452698445421.853751395
2230199.83239982445487.6594550962230234.76622088445668.706205665
2230248.44525801445754.200187743
#Sta/Elev= 30
       0 2138.38     9.8 2136.78    19.3  2136.3    99.2 2134.94   126.7 2132.82
   145.2 2132.21   168.8 2130.65   218.4 2129.93   248.2 2130.41   258.2 2129.83
     278 2129.79   317.8 2128.53   331.1 2127.35   357.5 2127.02   368.3 2126.44
   487.4 2126.28     492 2126.06   496.6 2125.09   501.2 2124.51   505.8  2125.1
   524.2 2126.19   538.1 2125.47   558.8 2126.52   660.6 2125.67   758.2 2126.09
   765.4 2126.52   777.2 2128.77   790.6 2130.07   802.8 2130.91   811.9 2130.44
#Mann= 5 ,-1,0
       0     .08       0      70     .07       0   496.6    .045       0
   505.8     .07       0  745.33     .06       0
#XS Ineff= 2 , 0
                             600            2128
Permanent Ineff=
       F       F
Bank Sta=496.6,505.8
XS Rating Curve= 0 ,0
Exp/Cntr(USF)=0,0
Exp/Cntr=0.3,0.1

Type RM Length L Ch R = 1 ,1219    ,41,41,41
BEGIN DESCRIPTION:
Structure XS 4
END DESCRIPTION:
XS GIS Cut Line= 4
2230211.53742839444831.7858878242229948.75970317445290.090166887
2230228.97291727445674.9163142522230247.48060704445759.858800374
#Sta/Elev= 30
       0 2127.09    95.2 2127.77     163 2126.75   236.8 2126.77   278.3 2126.32
   296.7  2125.6   361.3 2125.75   421.2 2124.81   448.9 2126.16   507.5 2126.43
   547.3 2125.37   561.8 2124.09   596.4 2123.28   610.3 2123.73  614.87 2122.68
   618.8 2122.23   622.4 2122.67   631.1 2123.91   681.8 2124.15     742 2125.46
   769.6 2125.05   833.9 2125.91   870.8 2125.94   885.1 2125.34   973.9 2126.08
  1027.1 2125.98  1035.3 2126.35  1047.6 2128.45  1076.2 2130.85  1091.3 2130.13
#Mann= 7 ,-1,0
       0     .08       0     190     .07       0     290     .08       0
     420     .07       0  614.87    .045       0   622.4     .07       0
 1014.33     .06       0
#XS Ineff= 2 , 0
          479.32 2127.38  836.96         2126.69
Permanent Ineff=
       F       F
Bank Sta=614.87,622.4
XS Rating Curve= 0 ,0
Exp/Cntr(USF)=0,0
Exp/Cntr=0.5,0.3

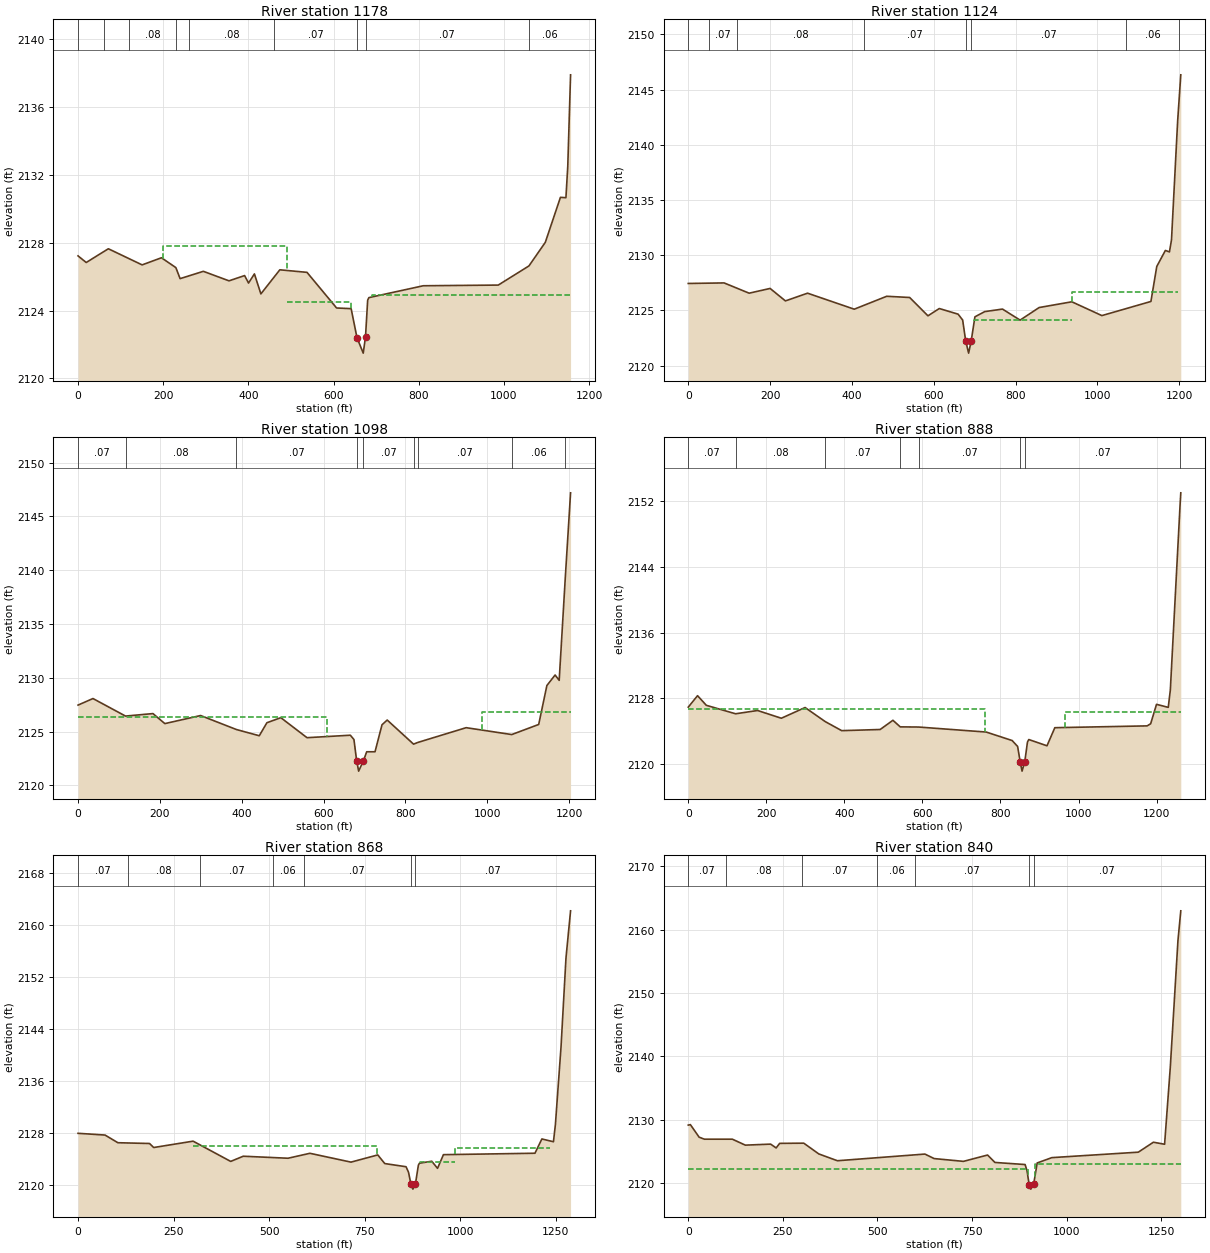
Type RM Length L Ch R = 1 ,1178    ,53.7,53.7,53.7
BEGIN DESCRIPTION:
Structure XS 3; 14.5 ft between structure and xs
END DESCRIPTION:
XS GIS Cut Line= 4
2230192.44090852444796.4543872492229908.49151823445299.592780568
2230193.68630059445675.0784874632230232.29345453445775.332548508
#Sta/Elev= 30
       0 2127.22    19.2 2126.83    71.2 2127.64   150.5 2126.69   195.9 2127.11
   229.7 2126.53   239.7 2125.88   294.3 2126.31   354.5 2125.75   391.2 2126.06
   400.4 2125.62   414.2 2126.16   429.4 2124.98   473.9  2126.4   537.7 2126.25
   607.2 2124.15   641.4 2124.11   655.1  2122.4   669.8 2121.49   675.1 2122.45
   680.2 2124.61     683 2124.76   810.8 2125.46   986.9  2125.5    1059 2126.63
  1097.4 2128.02  1132.9 2130.67  1145.8 2130.65  1150.1 2132.48  1156.7 2137.89
#Mann= 9 ,-1,0
       0     .08       0      60     .07       0     120     .08       0
     230     .07       0     260     .08       0     460     .07       0
   655.1    .045       0   675.1     .07       0 1059.25     .06       0
#XS Ineff= 4 ,-1
       0  200.11  2124.5  200.11  490.14 2127.82  490.14     640  2124.5
     690  1156.7  2124.9
Permanent Ineff=
       F       F       F       F
Bank Sta=655.1,675.1
XS Rating Curve= 0 ,0
Exp/Cntr(USF)=0,0
Exp/Cntr=0.5,0.3

Type RM Length L Ch R = 1 ,1124    ,25.9,25.9,25.9
BEGIN DESCRIPTION:
Structure XS 2; 20.5 ft between structure and xs
END DESCRIPTION:
XS GIS Cut Line= 3
2230189.12037127444793.8014299132229869.05461116 445324.33844861
2230220.25517283445791.360472112
#Sta/Elev= 30
       0 2127.44    87.6 2127.49   148.8 2126.56   200.1 2126.99   237.5 2125.86
   291.6 2126.56   405.7 2125.11   485.1 2126.28   541.2 2126.17   585.9 2124.51
   613.6 2125.17   659.6 2124.66   670.7 2124.13   678.22122.226   685.3 2121.13
  691.64 2122.24   700.7 2124.42   724.6 2124.89   768.1 2125.12   811.1 2124.12
   857.7 2125.26   937.6 2125.78    1011 2124.53  1130.9 2125.81  1145.2 2128.98
  1166.2 2130.43  1176.2  2130.3  1181.2  2131.4  1196.2 2142.14  1203.9 2146.34
#Mann= 8 ,-1,0
       0     .08       0      50     .07       0     120     .08       0
     430     .07       0   678.2    .045       0  691.64     .07       0
 1069.61     .06       0 1199.61      .1       0
#XS Ineff= 4 ,-1
       0     670    2124     699  938.59  2124.1  938.59 1196.51 2126.71
 1196.51  1203.9  2124.1
Permanent Ineff=
       F       F       F       F
Bank Sta=678.2,691.64
XS Rating Curve= 0 ,0
Exp/Cntr(USF)=0,0
Exp/Cntr=0.5,0.3

Type RM Length L Ch R = 1 ,1098    ,210.3,210.3,210.3
BEGIN DESCRIPTION:
Structure XS 1
END DESCRIPTION:
XS GIS Cut Line= 3
2230164.21253001 444801.896478322229844.14676991445332.433497018
2230195.34733158445799.455520519
#Sta/Elev= 30
       0 2127.46    36.5 2128.07     116 2126.44   183.1 2126.67   212.2 2125.74
   299.6 2126.49     387 2125.19     443 2124.61   461.6 2125.82   495.7 2126.29
   559.7 2124.43   665.6 2124.66   674.4 2124.26  681.02 2122.28   685.9 2121.32
   697.3 2122.26   705.6 2123.12   725.9 2123.12     743 2125.63   755.7 2126.07
   820.1 2123.83   830.7 2123.99   948.7 2125.36  1060.1 2124.72    1126 2125.66
    1146 2129.28  1166.1 2130.26  1176.1 2129.76  1191.1 2139.37  1203.9  2147.2
#Mann= 9 ,-1,0
       0     .07       0     116     .08       0     387     .07       0
  681.02    .045       0   697.3     .07       0   820.1     .06       0
   830.7     .07       0  1060.1     .06       0  1191.1      .1       0
#XS Ineff= 2 , 0
          608.11 2126.32  987.49         2126.81
Permanent Ineff=
       F       F
Bank Sta=681.02,697.3
XS Rating Curve= 0 ,0
Exp/Cntr(USF)=0,0
Exp/Cntr=0.3,0.1

Type RM Length L Ch R = 1 ,888     ,20.1,20.1,20.1
BEGIN DESCRIPTION:
Structure XS 4
END DESCRIPTION:
XS GIS Cut Line= 3
2230148.56417366444793.670891593 2229715.8028858445501.825726268
2229976.06491906445846.824235469
#Sta/Elev= 30
       0 2126.94    23.8 2128.33    46.3 2127.16   121.3 2126.13   177.6 2126.53
   238.5 2125.59   299.4 2126.89     351 2125.18   393.2 2124.08   491.7 2124.22
   524.5 2125.34   543.2 2124.54   590.1 2124.52   763.5 2123.91   829.9 2122.88
     844 2122.16   850.5 2120.31   855.4 2119.16  862.33 2120.31   869.2 2122.69
   872.6    2123   919.3 2122.24   939.3 2124.44  1175.9 2124.66  1184.9 2124.92
  1199.9 2127.28    1230 2126.91  1235.3 2129.01    1260 2151.28  1262.1 2152.99
#Mann= 8 ,-1,0
       0     .07       0   121.3     .08       0     351     .07       0
   543.2     .06       0   590.1     .07       0   850.5    .045       0
  862.33     .07       0    1260      .1       0
#XS Ineff= 2 , 0
             760 2126.77  964.16         2126.32
Permanent Ineff=
       F       F
Bank Sta=850.5,862.33
XS Rating Curve= 0 ,0
Exp/Cntr(USF)=0,0
Exp/Cntr=0.5,0.3

Type RM Length L Ch R = 1 ,868     ,28.5,28.5,28.5
BEGIN DESCRIPTION:
Structure XS 3; 12.2 ft between structure and xs
END DESCRIPTION:
XS GIS Cut Line= 3
2230136.34565018444788.1605108432229696.03938023445509.481131955
2229967.46294168445860.575008236
#Sta/Elev= 30
       0 2127.89    70.7 2127.62   104.3 2126.44   187.1 2126.32     198  2125.7
   301.1 2126.68   399.5 2123.56   432.3 2124.36   549.5 2124.05   606.8 2124.81
   714.3 2123.45   784.4 2124.56   802.6 2123.23   858.4 2122.74   864.9 2121.88
   871.12120.078   876.3 2119.29   882.9 2120.07   890.6 2122.97   893.4 2123.28
   925.6 2123.59   940.8 2122.49   956.2  2124.6  1195.7 2124.82  1213.8 2127.02
  1244.1 2126.59  1249.2 2129.23  1263.9 2141.17  1276.9 2154.91  1288.9 2162.17
#Mann= 7 ,-1,0
       0     .07       0     130     .08       0     320     .07       0
     510     .06       0     590     .07       0   871.1    .045       0
   882.9     .07       0
#XS Ineff= 6 ,-1
       0  300.08  2122.5  300.08  782.03 2125.91  782.03     859  2122.5
     895  987.18  2123.5  987.18 1236.15 2125.56 1236.15  1288.9  2123.5
Permanent Ineff=
       F       F       F       F       F       F
Bank Sta=871.1,882.9
XS Rating Curve= 0 ,0
Exp/Cntr(USF)=0,0
Exp/Cntr=0.5,0.3

Type RM Length L Ch R = 1 ,840     ,52.5,52.5,52.5
BEGIN DESCRIPTION:
Structure XS 2; 10 ft between structure and xs
END DESCRIPTION:
XS GIS Cut Line= 3
2230117.52385779444772.355307578 2229676.7983219 445530.95906495
2229935.78947823 445867.11337684
#Sta/Elev= 30
       0 2129.16     5.6 2129.24    28.7 2127.26    42.5 2126.94   116.6 2126.94
   150.8    2126   217.7 2126.16   232.3 2125.56   241.5 2126.28   305.3 2126.31
   345.1 2124.61   394.2 2123.54   625.5 2124.59   649.9 2123.88   727.3 2123.44
     791 2124.44   810.5 2123.27   890.2 2122.94   895.3 2121.98   901.2 2119.69
   905.4 2119.06   912.92119.851   922.2 2123.19   960.9 2124.03  1189.4 2124.89
  1229.3 2126.46  1258.9 2126.14    1274 2138.31  1294.2 2158.27  1301.7 2162.97
#Mann= 7 ,-1,0
       0     .07       0     100     .08       0     300     .07       0
     500     .06       0     600     .07       0   901.2    .045       0
   912.9     .07       0
#XS Ineff= 2 , 0
             898  2122.3     916         2122.95
Permanent Ineff=
       F       F
Bank Sta=901.2,912.9
XS Rating Curve= 0 ,0
Exp/Cntr(USF)=0,0
Exp/Cntr=0.5,0.3

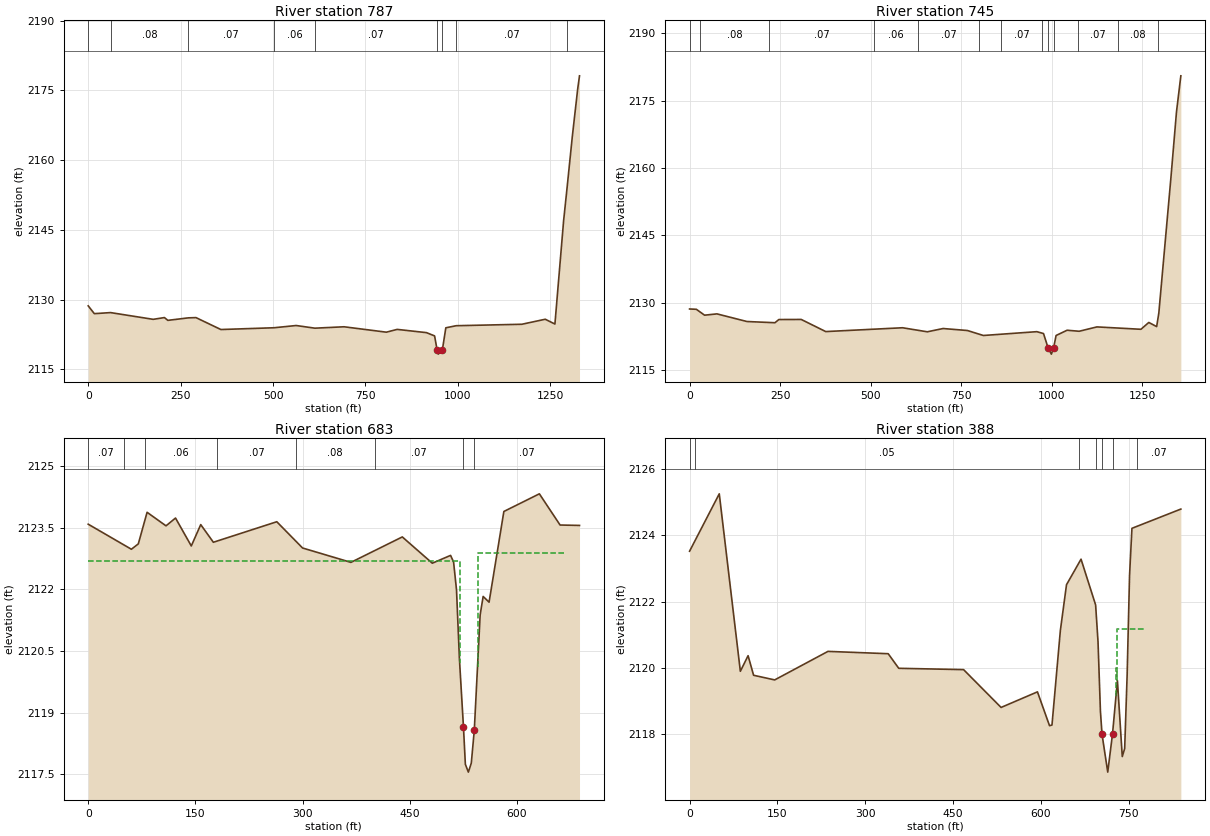
Type RM Length L Ch R = 1 ,787     ,41.8,41.8,41.8
BEGIN DESCRIPTION:
Structure XS 1
END DESCRIPTION:
XS GIS Cut Line= 3
2230096.56185393444767.0312719262229636.57883996 445557.89390924
2229854.81551712445909.744408688
#Sta/Elev= 30
       0 2128.68    16.5    2127    60.4 2127.23   175.8 2125.78   206.1 2126.16
   215.4 2125.56     271  2126.1   291.5 2126.15   358.8 2123.59   502.6 2123.97
   562.4 2124.45   613.2 2123.88     692 2124.18   806.4 2123.02   835.7 2123.62
   914.9 2122.92   936.9 2122.22   943.72119.218     947  2118.3   957.7 2119.09
   967.3 2123.96   995.4 2124.41  1172.9 2124.72  1236.2  2125.8  1262.4 2124.77
  1285.9 2146.98  1295.3 2154.09  1309.4 2165.05  1323.9 2175.26  1328.9 2178.14
#Mann= 9 ,-1,0
       0     .07       0    60.4     .08       0     271     .07       0
   502.6     .06       0   613.2     .07       0   943.7    .045       0
   957.7     .06       0   995.4     .07       0  1295.3      .1       0
Bank Sta=943.7,957.7
XS Rating Curve= 0 ,0
Exp/Cntr(USF)=0,0
Exp/Cntr=0.3,0.1

Type RM Length L Ch R = 1 ,745     ,62.3,62.3,62.3
BEGIN DESCRIPTION:
Structure XS 4
END DESCRIPTION:
XS GIS Cut Line= 3
2230079.78627355444751.3799202252229600.77427226445564.123004733
2229758.31349206  445938.7162607
#Sta/Elev= 30
       0 2128.62    18.7 2128.55    41.4 2127.24    75.6 2127.53   158.4 2125.83
   235.7 2125.56   246.5 2126.27   308.3 2126.29     376 2123.59   588.1 2124.44
   656.4 2123.54     700 2124.27     767 2123.83   811.2 2122.72   958.9 2123.57
   977.3 2123.15   989.9 2119.97     999 2118.57 1005.19 2119.99    1012 2122.72
  1042.4 2123.89  1075.7 2123.66  1124.8 2124.63  1246.3  2124.1    1268 2125.62
  1289.7  2124.7  1295.7 2127.72  1328.8 2157.57  1344.5 2172.54  1356.5 2180.53
#Mann= 13 ,-1,0
       0     .07       0      30     .08       0     220     .07       0
     510     .06       0     630     .07       0     800     .08       0
     860     .07       0   973.4     .06       0   989.9    .045       0
 1005.19     .06       0  1073.4     .07       0  1183.4     .08       0
  1293.4     .07       0
Bank Sta=989.9,1005.19
XS Rating Curve= 0 ,0
Exp/Cntr(USF)=0,0
Exp/Cntr=0.5,0.3

Type RM Length L Ch R = 1 ,683     ,294.5,294.5,294.5
BEGIN DESCRIPTION:
structure xs 3; 3.5 ft between structure and xs
END DESCRIPTION:
XS GIS Cut Line= 4
2229790.65943284445126.477429855 2229688.7670848445344.665846143
2229567.55744912445576.1337850842229519.25680922445755.442461441
#Sta/Elev= 30
       0 2123.59    60.4 2122.98    70.1 2123.11    82.4 2123.88   108.9 2123.55
   122.2 2123.74   144.3 2123.06   157.5 2123.58   175.2 2123.15     264 2123.65
   300.1 2123.01   367.8 2122.66   439.7 2123.28   481.7 2122.64   507.3 2122.83
   511.5 2122.67   515.6 2121.99   519.7  2120.3   525.3 2118.66     528 2117.74
   532.2 2117.55   536.3 2117.77   540.5 2118.57   548.7 2121.38   552.9 2121.83
   561.2 2121.69   581.9  2123.9   631.6 2124.33   660.6 2123.57   687.8 2123.56
#Mann= 8 ,-1,0
       0     .07       0      50     .05       0      80     .06       0
     180     .07       0  290.81     .08       0  400.81     .07       0
   525.3    .045       0   540.5     .07       0
#XS Ineff= 2 ,-1
       0     520  2122.7     545   667.4  2122.9
Permanent Ineff=
       F       F
Bank Sta=525.3,540.5
XS Rating Curve= 0 ,0
Exp/Cntr(USF)=0,0
Exp/Cntr=0.5,0.3

Type RM Length L Ch R = 1 ,388     ,151.8,151.8,151.8
BEGIN DESCRIPTION:
structure xs 2; 17.7 ft between structure and xs
END DESCRIPTION:
XS GIS Cut Line= 3
2229781.15718521 445111.516737022229324.48749965445348.500368092
2229241.29321018445661.856727089
#Sta/Elev= 30
       0 2123.52    50.7 2125.25    86.7  2119.9    99.9 2120.37   109.3 2119.78
   145.3 2119.64   236.3  2120.5   339.1 2120.43   357.1 2119.99   467.8 2119.95
   531.8 2118.81   593.9 2119.28   614.5 2118.26   618.7 2118.28     633 2121.13
   643.5 2122.51   668.3 2123.28   693.2  2121.9   697.3 2120.79   701.4  2118.7
704.09632118.006   713.9 2116.86   722.1 2118.02   730.4 2119.62   738.7 2117.33
   742.8 2117.57     747 2119.78   751.1 2122.78   755.2 2124.21   838.7 2124.79
#Mann= 7 ,-1,0
       0     .07       0      10     .05       0   664.5     .07       0
   694.5     .05       0704.0963    .045       0   722.1     .05       0
   764.5     .07       0
#XS Ineff= 4 ,-1
   32.68  655.77 2121.21  655.77     698    2120     728  730.46    2120
  730.46  777.12 2121.16
Permanent Ineff=
       F       F       F       F
Bank Sta=704.0963,722.1
XS Rating Curve= 0 ,0
Exp/Cntr(USF)=0,0
Exp/Cntr=0.5,0.3