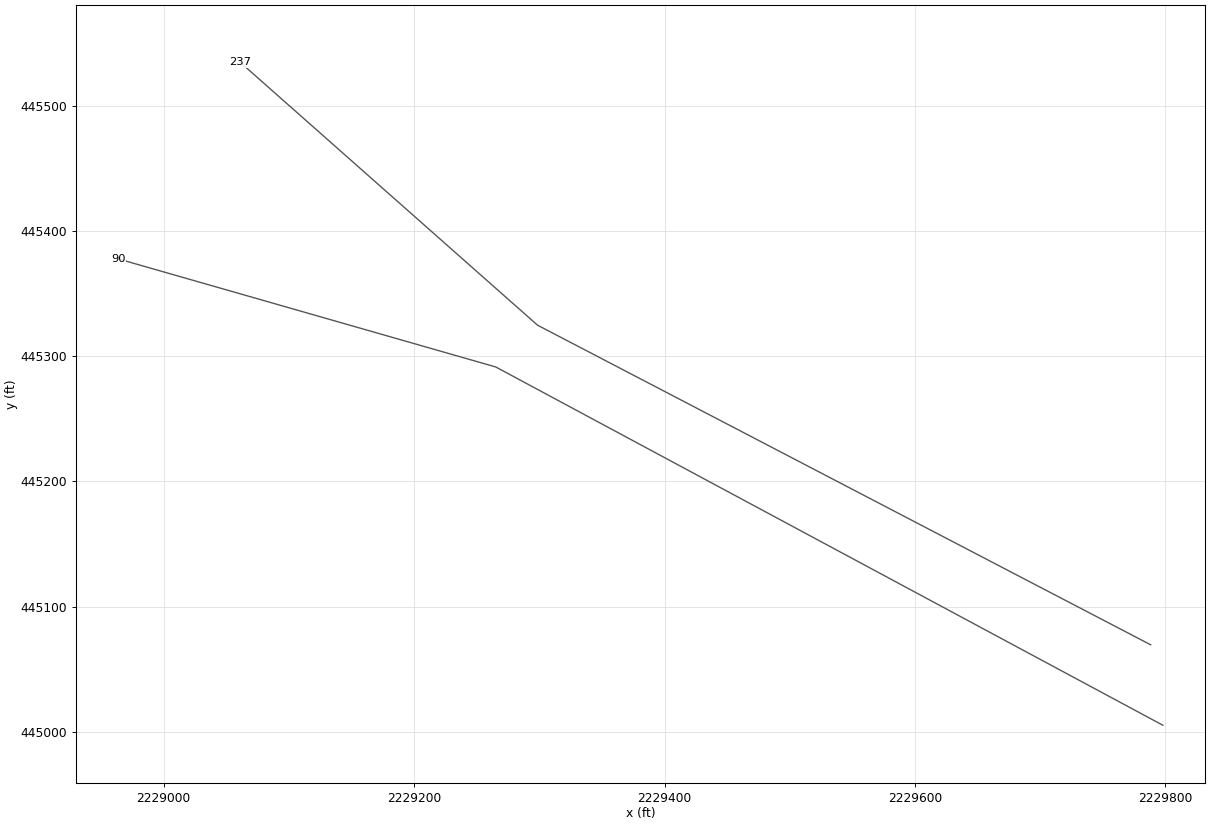
HEC-RAS study MARLNRN.prj: MARLNRN

--- MARLNRN.g01 (geometry) --- (continued)

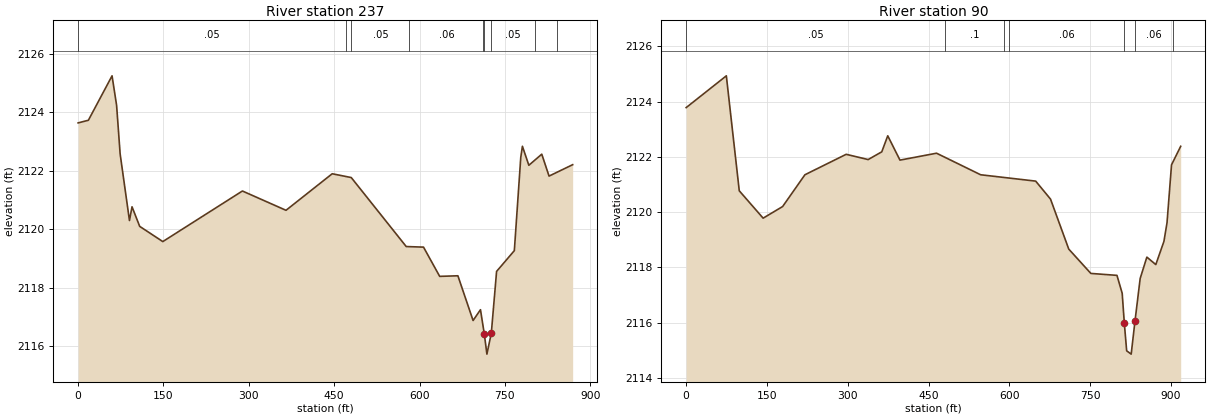
Type RM Length L Ch R = 1 ,237     ,146.2,146.2,146.2
BEGIN DESCRIPTION:
structure xs 1
END DESCRIPTION:
XS GIS Cut Line= 3
2229788.14119523445069.6126768632229298.55065915445324.817823108
 2229061.1057515445534.747744611
#Sta/Elev= 30
       0 2123.64      18 2123.73    59.6 2125.25    67.6 2124.24    73.8 2122.58
    90.2  2120.3    94.7 2120.77   108.2  2120.1   148.8 2119.58   288.7 2121.31
   365.3 2120.65   446.5  2121.9     480 2121.77   576.6 2119.41     607 2119.39
   635.4 2118.39   667.4 2118.41   694.1 2116.88   707.1 2117.25 713.9432116.403
   718.4 2115.73726.13962116.449   735.4 2118.56   766.6 2119.27   777.9 2122.46
   780.8 2122.84   792.1 2122.19   814.8 2122.57   827.6 2121.82   869.1 2122.21
#Mann= 9 ,-1,0
       0     .05       0     470      .1       0     480     .05       0
  582.11     .06       0  712.11     .05       0 713.943    .045       0
726.1396     .05       0  802.11     .07       0  842.11     .08       0
Bank Sta=713.943,726.1396
XS Rating Curve= 0 ,0
Exp/Cntr(USF)=0,0
Exp/Cntr=0.3,0.1

Type RM Length L Ch R = 1 ,90      ,,,
XS GIS Cut Line= 3
2229797.91880927445005.359784621 2229265.1903182445291.457482152
2228963.79689301445377.734226004
#Sta/Elev= 30
       0 2123.78    74.6 2124.93    98.6 2120.77   142.9 2119.78   179.1  2120.2
   220.5 2121.35   297.1 2122.09   337.9  2121.9   363.2 2122.18   374.3 2122.76
     397 2121.88   464.9 2122.13   546.8 2121.35     649 2121.12   676.5 2120.47
   710.4 2118.66   751.4 2117.78   799.9 2117.71   809.6 2117.06 813.4872115.994
   817.9 2114.98   826.3 2114.86 833.2872116.046     843  2117.6   855.4 2118.37
     872  2118.1   887.1 2118.94   892.8 2119.61   901.2 2121.71   918.2 2122.38
#Mann= 7 ,-1,0
       0     .05       0     480      .1       0     590     .07       0
     600     .06       0 813.487    .045       0 833.287     .06       0
  904.69     .07       0
Bank Sta=813.487,833.287
XS Rating Curve= 0 ,0
Exp/Cntr(USF)=0,0
Exp/Cntr=0.3,0.1
LCMann Table=0

Chan Stop Cuts=-1
Use User Specified Reach Order=0
Composite Channel Slope=5